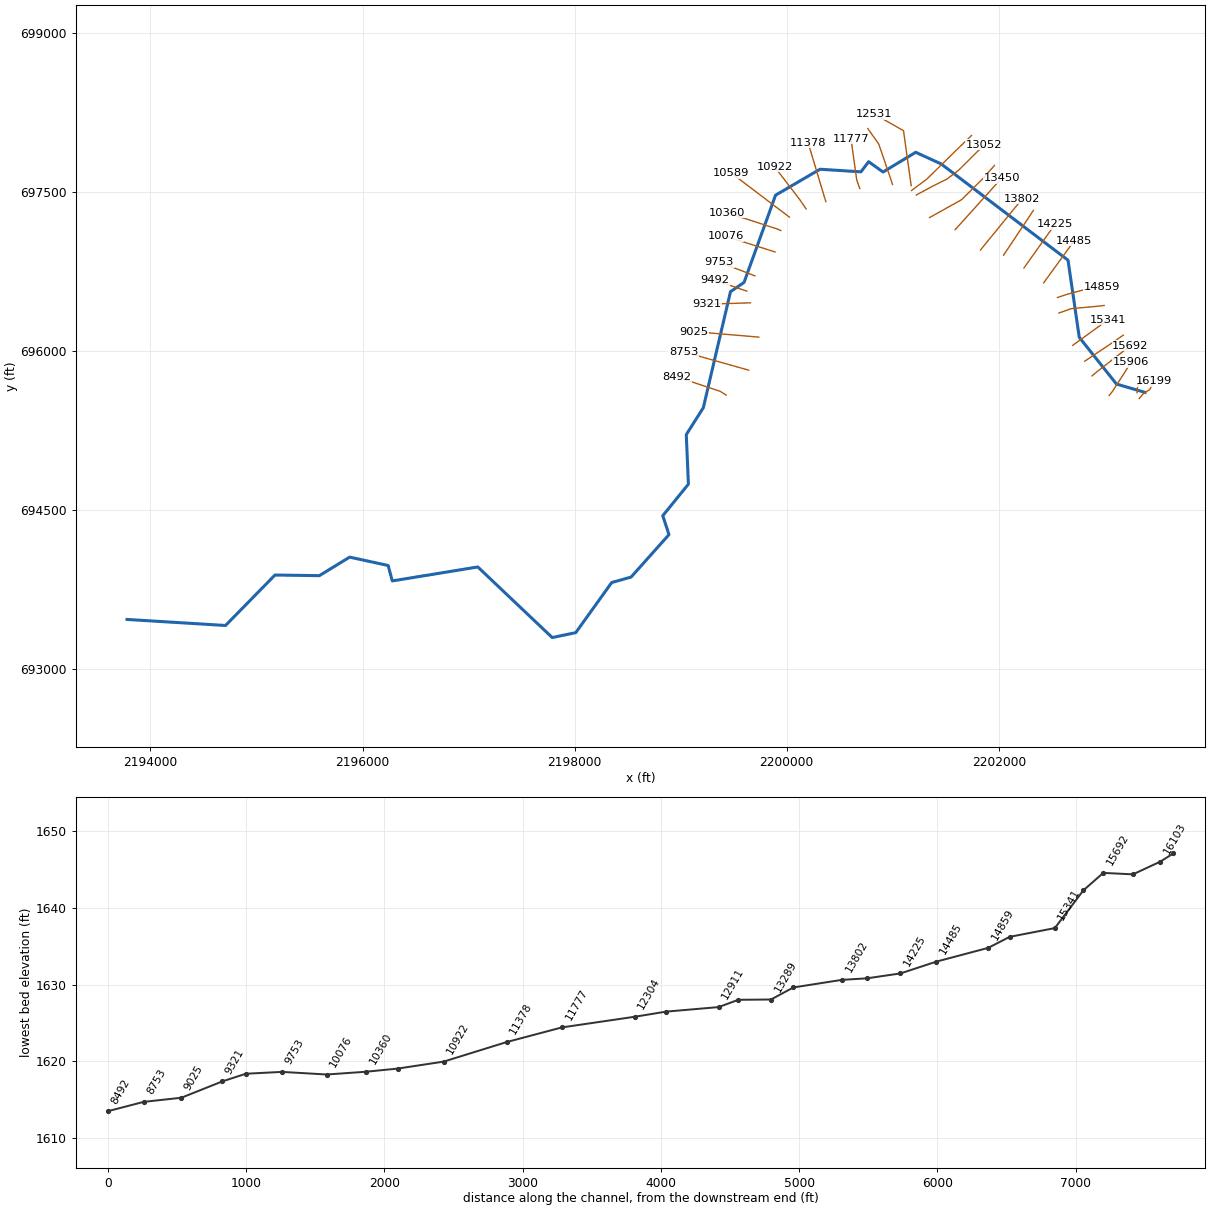
--- GRASSYRN.prj (project) ---

Proj Title=GRASSYRN
Current Plan=p01
Default Exp/Contr=0,0
English Units
Geom File=g01
Flow File=f01
Plan File=p01
BEGIN DESCRIPTION:
--------- MODELED AS PART OF WVEMD CTP PROGRAM, 2023----------
Stream Name:GRASSYRN
Flood Zone:  AFH
Upshur County, WV
HEC-RAS Version: RAS 6.3
Vertical Datum: NAVD88
Projection: NAD 1983 StatePlane West Virginia S FIPS 4702 (US Feet)
Terrain: 1-meter LIDAR (FEMA Region III 3DEP collected 2016-2018)
Land Use: 2019 NLCD
Hydrologic Method:
WV SIR2010-5033 regression equations
Additional Model Notes:
Main stem is BUCKHANR_U; tie-in check needed after main stem is finished
END DESCRIPTION:
DSS Export Rating Curves= 0
DSS Export Rating Curve Sorted= 0
DSS Export Volume Flow Curves= 0
DXF OffsetX= 0
DXF OffsetY= 0
DXF ScaleX= 0
DXF ScaleY= 0

--- GRASSYRN.p01 (plan) ---

Plan Title=Floodplain
Program Version=6.31
Short Identifier=Floodplain
Geom File=g01
Flow File=f01
Subcritical Flow
K Sum by GR= 0
Std Step Tol= 0.01
Critical Tol= 0.01
Num of Std Step Trials= 20
Max Error Tol= 0.3
Flow Tol Ratio= 0.001
Split Flow NTrial= 30
Split Flow Tol= 0.02
Split Flow Ratio= 0.02
Log Output Level= 0
Friction Slope Method= 1
Unsteady Friction Slope Method= 2
Unsteady Bridges Friction Slope Method= 1
Parabolic Critical Depth
Global Vel Dist= 0 , 0 , 0
Global Log Level= 0
CheckData=True
Encroach Param=-1 ,0,0, 0
Mapping Interval=1HOUR
Computation Time Step Use Courant=        0
Computation Time Step Use Time Series=    0
Computation Time Step Count To Double=0
Computation Time Step Max Doubling=0
Computation Time Step Max Halving=0
Computation Time Step Residence Courant=0
Run HTab= 0
Run UNet= 0
Run Sediment= 0
Run PostProcess= 0
Run WQNet= 0
Run RASMapper=-1
UNET Theta= 0
UNET Theta Warmup= 0
UNET ZTol= 0
UNET ZSATol= 0
UNET MxIter= 0
UNET Max Iter WO Improvement= 0
UNET MaxInSteps= 0
UNET DtIC= 0
UNET DtMin= 0
UNET MaxCRTS= 0
UNET WFStab= 0
UNET SFStab= 0
UNET WFX= 1
UNET SFX= 1
UNET Gravity=32.17405
UNET 1D Methodology=Finite Difference
UNET DSS MLevel= 1
UNET Pardiso=0
UNET DZMax Abort= 0
UNET Use Existing IB Tables= 0
UNET Froude Reduction=False
UNET Froude Limit= 0
UNET Froude Power= 0
UNET D1 Cores= 0
UNET WindReference=Eulerian
UNET WindDragFormulation=Hsu (1988)
UNET D2 Coriolis=0
UNET D2 Cores= 0
UNET D2 Theta= 1
UNET D2 Theta Warmup= 1
UNET D2 Z Tol= 0.01
UNET D2 Volume Tol= 0.01
UNET D2 Max Iterations= 20
UNET D2 Equation= 0
UNET D2 RampUpFraction=0.1
UNET D2 TimeSlices= 1
UNET D2 Turbulence Formulation=Non-Conservative (original)
UNET D2 Eddy Viscosity=0.3
UNET D2 Transverse Eddy Viscosity=0.1
UNET D2 Smagorinsky Mixing=0
UNET D2 BCVolumeCheck=0
UNET D2 Cores=0
UNET D2 SolverType=PARDISO (Direct)
UNET D2 Minimum Iterations= 3
UNET D2 Maximum Iterations= 30
UNET D2 Restart Number= 10
UNET D2 Relaxation Coeff=1.3
UNET D2 SOR Precondition Iterations= 10
UNET D2 ILUT Maximum Fill= 8
UNET D2 ILUT Tolerance=1E-08
UNET D2 Convergence Tolerance=0.00001
UNET D1D2 MaxIter= 0
UNET D1D2 ZTol=0.01
UNET D1D2 QTol=0.1
UNET D1D2 MinQTol=1
Write IC File= 0
Write IC File at Fixed DateTime=0
Write IC File at Sim End=0
Echo Input=False
Echo Parameters=False
Echo Output=False
Write Detailed= 0
HDF Write Warmup=0
HDF Write Time Slices=0
HDF Flush=0
HDF Compression= 1
HDF Chunk Size= 1
HDF Spatial Parts= 1
HDF Use Max Rows=0
HDF Fixed Rows= 1
Calibration Method= 0
Calibration Iterations= 20
Calibration Max Change=0.05
Calibration Tolerance=0.2
Calibration Maximum=1.5
Calibration Minimum=0.5
Calibration Optimization Method= 1
WQ AD Non Conservative
WQ ULTIMATE=-1
WQ Max Comp Step=1HOUR
WQ Output Interval=15MIN
WQ Output Selected Increments= 0
WQ Create Restart=0
WQ Fixed Restart=0
WQ System Summary=0
WQ Write To DSS=0
Sorting and Armoring Iterations= 10
XS Update Threshold= 0.02
Bed Roughness Predictor= 0
Hydraulics Update Threshold= 0.02
Energy Slope Method= 1
Volume Change Method= 1
Sediment Retention Method= 0
Sediment TS Multiplier= 1
Warm Up Method= 0
XS Weighting Method= 0
Number of US Weighted Cross Sections= 1
Number of DS Weighted Cross Sections= 1
Upstream XS Weight=0
Main XS Weight=1
Downstream XS Weight=0
Number of DS XS's Weighted with US Boundary= 1
Upstream Boundary Weight= 1
Weight of XSs Associated with US Boundary= 0
Number of US XS's Weighted with DS Boundary= 1
Downstream Boundary Weight= 0.5
Weight of XSs Associated with DS Boundary= 0.5
Percentile Method= 0
Sediment Output Level= 3
Mass or Volume Output= 0
Output Increment Type= 1
Profile and TS Output Increment= 1
Transport Output Increment 1
XS Output Flag= 0
XS Output Increment= 10
Read HDF5 Sediment Hotstart= 0
Sediment Hotstart Type= 0
Write Gradation File= 0
Read Gradation Hotstart= 0
Write HDF5 File= 1
Write Binary Output= 1
Write DSS Sediment File= 0
DSS Sediment Output Type= 1
SV Curve= 0
Specific Gage Flag= 0
Subcell Erosion Methods= 0
Subcell Deposition Methods= 0
Advection Scheme= 1
Matrix Solver= 0
Implicit Weighting Factor= 1
Maximum Outer Loop Convergence Iterations= 5
Convergence Maximum Absolute= 0.001
Convergence RMSE= 0.0001
Grain Fractions Max Abs Error= 0.001
Max Subgrid Regions= 1
Max Subgrid Length Scale= 3.402823E+38
Initial Layer Thickness= 3.402823E+38
Min Layer Thickness= 3.402823E+38
Max Layer Thickness= 3.402823E+38
Number of Layers= 5

--- GRASSYRN.f01 (steady flow) ---

Flow Title=Flows
Program Version=6.31
Number of Profiles= 1
Profile Names=01pct
River Rch & RM=GRASSYRN,Main            ,16199
     332
River Rch & RM=GRASSYRN,Main            ,14859
     371
River Rch & RM=GRASSYRN,Main            ,12531
     564
River Rch & RM=GRASSYRN,Main            ,9025
     632
River Rch & RM=GRASSYRN,Main            ,5068
     734
River Rch & RM=GRASSYRN,Main            ,3877
     841
Boundary for River Rch & Prof#=GRASSYRN,Main            , 1
Up Type= 0
Dn Type= 3
Dn Slope=0.01963
DSS Import GetInterval= 0
DSS Import GetPeak= 0
DSS Import FillOption= 0

--- GRASSYRN.g01 (geometry) ---

Geom Title=Geometry
Program Version=6.31

River Reach=GRASSYRN        ,Main
Reach XY= 30
2203379.70300002695606.8359999952203109.45000003695686.131999999
     2202758.985696126.5949999992202653.04700004696853.595000014
2201456.76800004697761.4210000042201216.61900005697871.251000002
2200908.47800003697685.3299999982200772.57900001697782.797000021
     2200700.008697687.018000022     2200314.001697711.570999995
2199894.77100001697466.6720000212199597.67600003696644.122999996
     2199469.818 696556.84300001     2199213.558695462.266000018
2199052.99100003695208.9820000082199073.02300002694741.790999994
2198831.38600005 694444.23800002     2198889.735694265.729000017
     2198532.402693865.4710000012198349.34299999693813.819000006
      2198010.84693341.334000006     2197788.748693295.090000004
     2197086.902693960.8209999952196280.46400003693829.128999993
     2196241.517693974.6720000212195878.20300001694053.567000017
2195592.81200002693878.8350000082195174.32600001      693884.787
2194707.79299998693408.925999999     2193778.905      693465.929

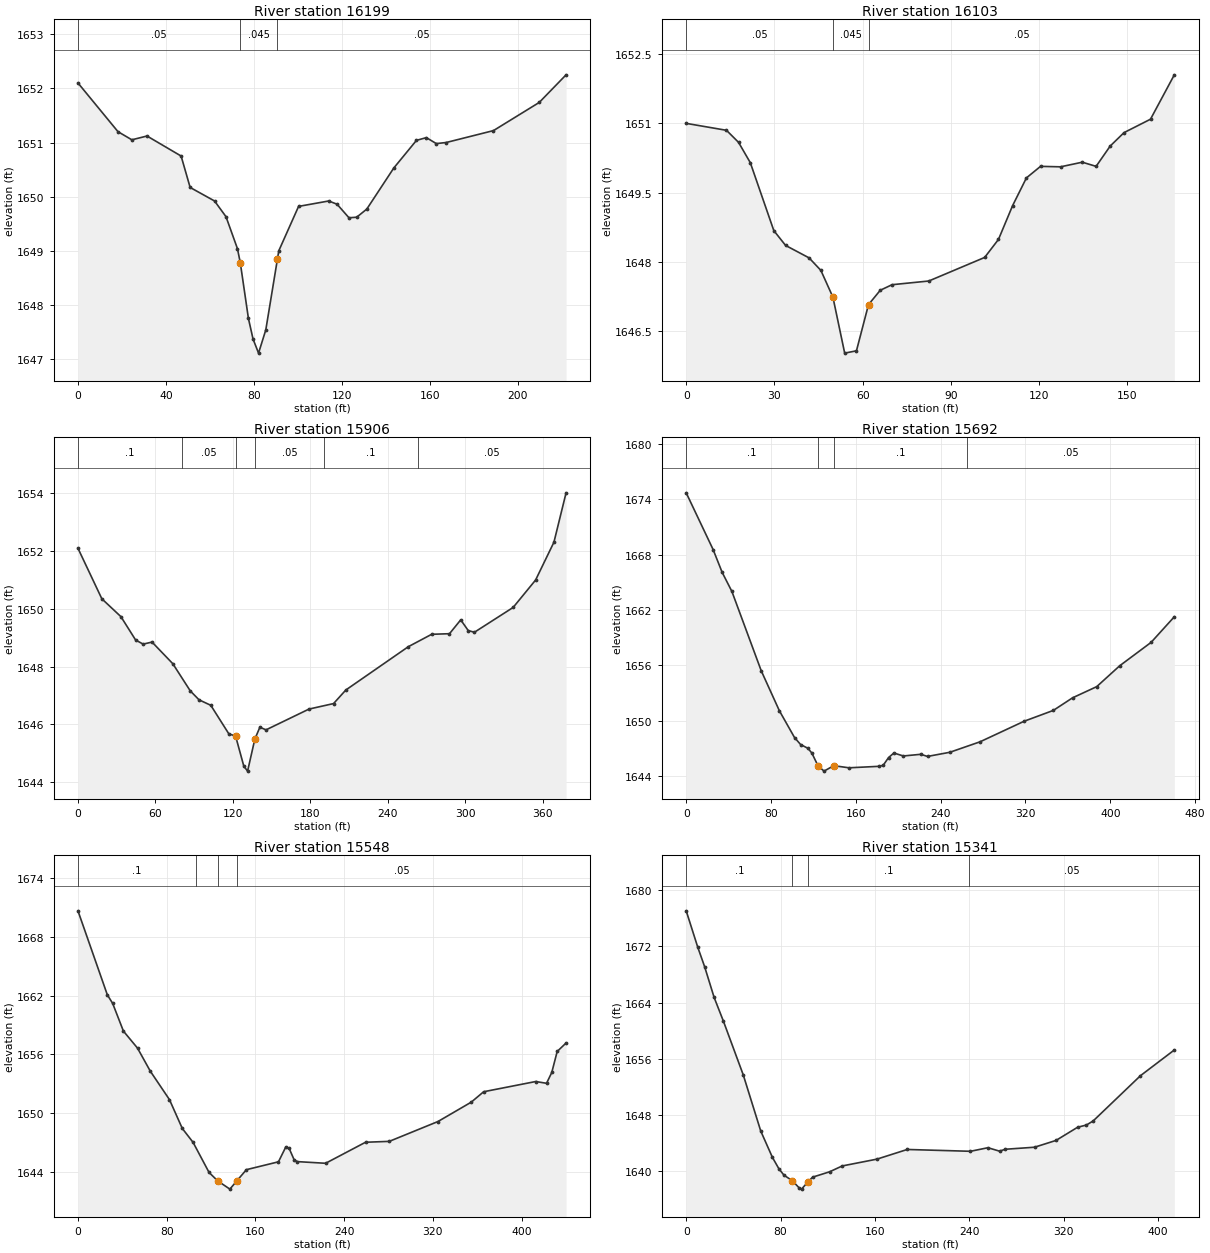
Type RM Length L Ch R = 1 ,16199   ,87.2,95.9,108.6
XS GIS Cut Line= 5
2203324.62822468 695548.925881352203363.34143727695596.137116214
2203375.30161676695605.8941047522203421.56862693695631.388171579
2203464.37347987695713.535720242
#Sta/Elev= 30
       0  1652.1    18.2  1651.2    24.5 1651.05    31.4 1651.12    46.9 1650.75
      51 1650.17    62.1 1649.92    67.3 1649.63    72.5 1649.04    73.8 1648.78
    77.5 1647.75    79.6 1647.37    82.1 1647.11    85.4 1647.54    90.7 1648.85
    91.3    1649   100.3 1649.82     114 1649.92   117.8 1649.86   123.2 1649.61
   126.7 1649.62   131.3 1649.77   143.6 1650.53   153.9 1651.04   158.4 1651.09
   162.9 1650.98   167.4    1651   188.9 1651.22   209.7 1651.74   221.9 1652.25
#Mann= 3 ,-1,0
       0     .05       0    73.8    .045       0    90.7     .05       0
Bank Sta=73.8,90.7
XS Rating Curve= 0 ,0
Exp/Cntr(USF)=0,0
Exp/Cntr=0.3,0.1

Type RM Length L Ch R = 1 ,16103   ,202.1,196.8,190.8
XS GIS Cut Line= 4
2203303.58947203695603.4743407352203306.61168185695644.490045464
2203311.36086871695684.6422616722203382.59867166695729.975409004
#Sta/Elev= 27
       0    1651    13.7 1650.85    17.8 1650.59    21.8 1650.15    29.8 1648.68
    33.8 1648.36    41.8 1648.09    45.8 1647.82    49.9 1647.24    53.9 1646.03
    57.9 1646.08      62 1647.08      66 1647.39      70 1647.51    82.5 1647.59
   101.5  1648.1   106.2 1648.49     111 1649.22   115.7 1649.82   120.5 1650.07
   127.3 1650.06   134.7 1650.16   139.4 1650.07   144.2 1650.51   148.9  1650.8
   157.9 1651.09     166 1652.05
#Mann= 3 ,-1,0
       0     .05       0    49.9    .045       0      62     .05       0
Bank Sta=49.9,62
XS Rating Curve= 0 ,0
Exp/Cntr(USF)=0,0
Exp/Cntr=0.3,0.1

Type RM Length L Ch R = 1 ,15906   ,217.6,214.6,209.3
XS GIS Cut Line= 4
2203040.51237208695577.9637609172203072.41938495695617.081917852
2203182.29505509695787.9726974122203248.84821231 695893.18503741
#Sta/Elev= 30
       0  1652.1    18.5 1650.35    33.3 1649.73    44.7 1648.92    50.5 1648.78
    57.4 1648.85    73.5  1648.1      87 1647.16    93.8 1646.85   102.9 1646.66
   116.9 1645.67   122.11645.595   128.5 1644.55   131.4 1644.38     1371645.484
   140.9  1645.9   145.7 1645.81     179 1646.53     198 1646.72   207.5 1647.19
   255.9 1648.69     274 1649.12   287.8 1649.14   296.5 1649.62   302.3 1649.25
   307.1 1649.19   337.1 1650.05   354.5    1651   368.7 1652.31   378.1 1654.02
#Mann= 6 ,-1,0
       0      .1       0   80.48     .05       0   122.1    .045       0
     137     .05       0  190.48      .1       0  263.65     .05       0
Bank Sta=122.1,137
XS Rating Curve= 0 ,0
Exp/Cntr(USF)=0,0
Exp/Cntr=0.3,0.1

Type RM Length L Ch R = 1 ,15692   ,144.5,143.6,143.1
XS GIS Cut Line= 3
 2202878.9778997 695762.626758232202936.54905137695810.253933708
2203240.75977125 696047.29238399
#Sta/Elev= 30
       0 1674.68    25.4 1668.54    33.9 1666.08    43.1 1664.01    70.8 1655.42
    87.9  1651.1   102.2  1648.2   107.9 1647.45   114.8 1647.04   118.5 1646.53
  124.27 1645.16     130 1644.57   139.2 1645.16   153.5 1644.93     182 1645.09
   185.8  1645.2   190.9 1646.04   195.9 1646.53   204.8 1646.21   221.3 1646.39
   227.6 1646.16   248.7 1646.61   277.1 1647.74   318.8 1649.97   346.3 1651.14
   364.4  1652.5   387.2 1653.71   408.9 1655.97   438.5  1658.5   460.4 1661.27
#Mann= 4 ,-1,0
       0      .1       0  124.27    .045       0   139.2      .1       0
  264.72     .05       0
Bank Sta=124.27,139.2
XS Rating Curve= 0 ,0
Exp/Cntr(USF)=0,0
Exp/Cntr=0.3,0.1

Type RM Length L Ch R = 1 ,15548   ,205.7,207,207.7
XS GIS Cut Line= 4
 2202810.4053772695900.3018407072202857.12667347695932.546115596
2203032.16702287 696049.678379482203174.79102939696147.057120592
#Sta/Elev= 30
       0 1670.62    26.5 1662.07    31.3  1661.2      41 1658.38    53.7 1656.65
    65.2 1654.31    82.5 1651.41    94.1 1648.47   103.8 1647.06   118.2    1644
     1261643.139     137  1642.3     143 1643.11   151.9 1644.28   180.8 1645.08
   187.4 1646.59   190.4 1646.45   194.9 1645.29   197.8  1645.1   223.3 1644.93
   259.3 1647.07   280.7 1647.16   324.6 1649.18   354.6 1651.15   365.8 1652.21
   412.7 1653.25   422.5 1653.07   427.2 1654.17   432.1 1656.31   440.1 1657.17
#Mann= 4 ,-1,0
       0      .1       0  106.77     .05       0     126    .045       0
     143     .05       0
Bank Sta=126,143
XS Rating Curve= 0 ,0
Exp/Cntr(USF)=0,0
Exp/Cntr=0.3,0.1

Type RM Length L Ch R = 1 ,15341   ,329.4,326.2,317
XS GIS Cut Line= 2
2202696.98480566696050.6379956932203032.18969853696293.262049048
#Sta/Elev= 30
       0 1677.09     9.8  1671.9    15.6 1669.13    23.7 1664.72    31.6 1661.32
    48.4 1653.66    63.2 1645.66    73.1  1641.9    78.6 1640.27    82.9 1639.36
      90 1638.57    95.8 1637.54    97.8 1637.37   103.31638.428   107.2 1639.08
   121.5 1639.84   132.3 1640.68   161.7 1641.65   187.4 1643.03     241 1642.77
   255.8 1643.28   265.6 1642.79   270.5 1643.06   295.3 1643.35   313.5 1644.32
   331.8  1646.2   339.3 1646.52     345  1647.1   385.1 1653.56   413.8 1657.23
#Mann= 4 ,-1,0
       0      .1       0      90    .045       0   103.3      .1       0
     240     .05       0
Bank Sta=90,103.3
XS Rating Curve= 0 ,0
Exp/Cntr(USF)=0,0
Exp/Cntr=0.3,0.1

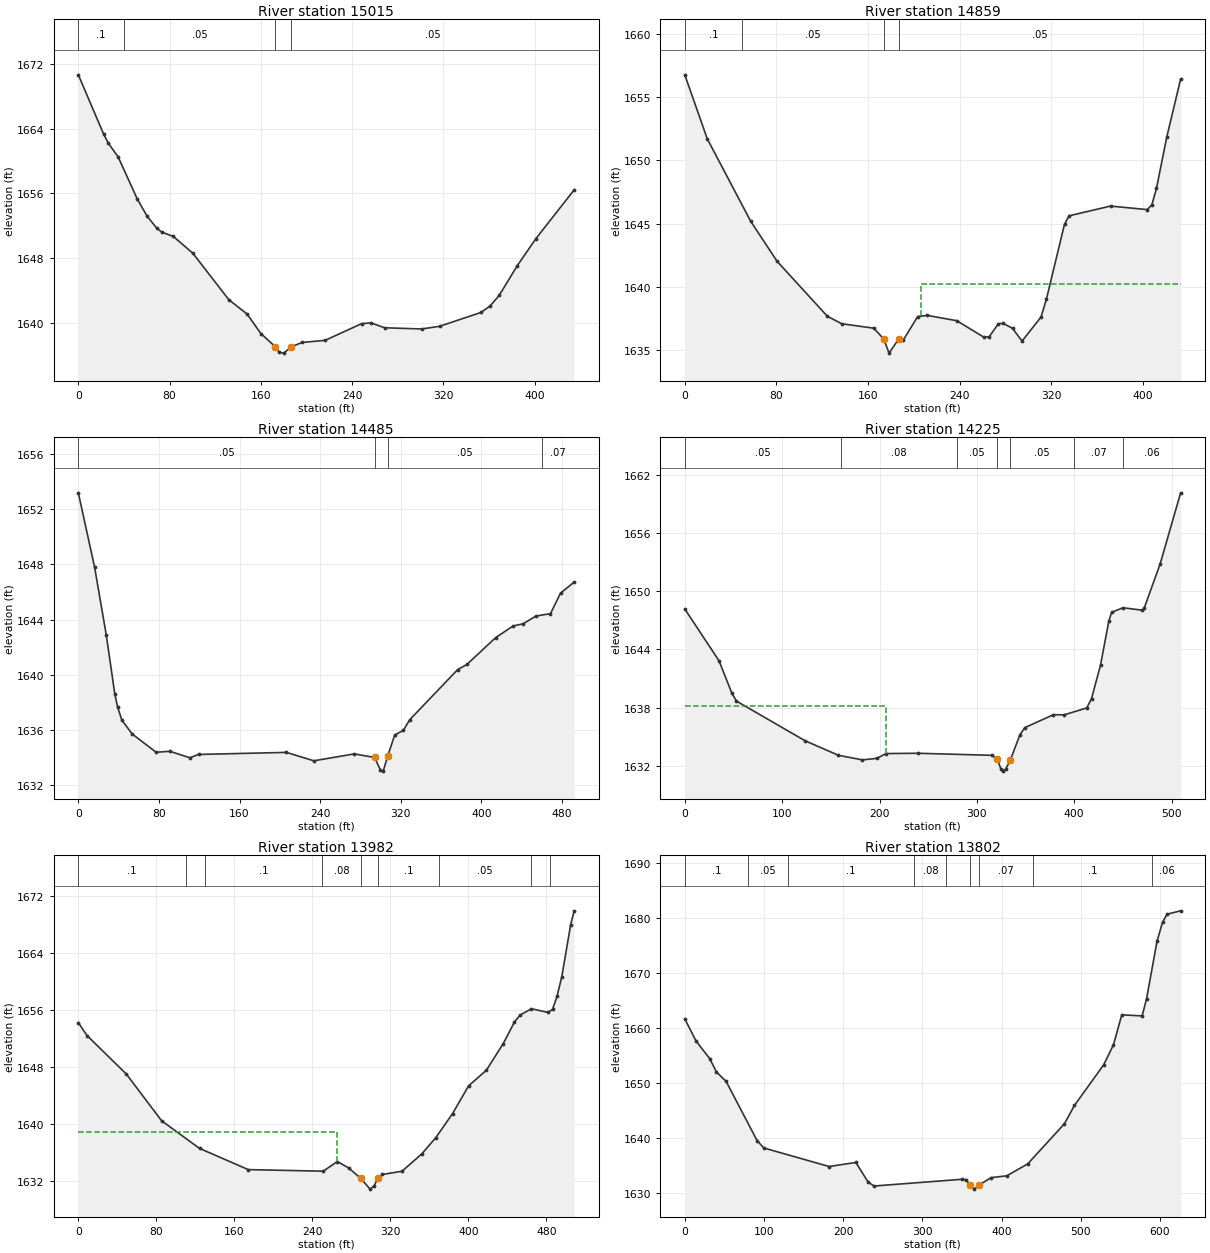
Type RM Length L Ch R = 1 ,15015   ,153.9,156,157.3
XS GIS Cut Line= 4
 2202567.2746192696355.8278730532202683.52948785696396.772984023
2202907.26527279696417.2455395092202993.54247091696426.750654555
#Sta/Elev= 30
       0 1670.68    22.2 1663.33    26.4  1662.2    34.9 1660.52    51.6 1655.33
    60.3 1653.18    68.8 1651.69      73 1651.22    83.3 1650.67   100.4  1648.6
   131.9 1642.85     148 1641.06   160.1 1638.64  172.64 1637.03   176.1 1636.34
   180.1 1636.23   186.8 1637.02   196.2 1637.55   216.3 1637.81   248.4 1639.88
   256.5 1639.97   268.5 1639.37   300.9 1639.22   316.7 1639.55   352.9 1641.26
   360.9 1642.05     369 1643.38   384.9 1647.07   401.2 1650.41   434.7 1656.44
#Mann= 4 ,-1,0
       0      .1       0      40     .05       0  172.64    .045       0
   186.8     .05       0
Bank Sta=172.64,186.8
XS Rating Curve= 0 ,0
Exp/Cntr(USF)=0,0
Exp/Cntr=0.3,0.1

Type RM Length L Ch R = 1 ,14859   ,364.8,374.2,380.4
XS GIS Cut Line= 4
2202553.56027596696501.7070336472202640.56863677696530.953541483
2202866.49790981696592.3712079382202973.24766341696601.145160289
#Sta/Elev= 30
       0 1656.76    19.6 1651.71    57.6 1645.19    80.6 1642.04   124.5  1637.7
     137 1637.11     165 1636.76  173.73 1635.91   178.4 1634.79   186.7  1635.9
   190.9 1635.83   203.3 1637.67   211.6 1637.77   237.5 1637.35   261.3 1636.04
     266  1636.1   273.8 1637.11   277.9 1637.14   286.2 1636.75   294.5 1635.74
   311.1 1637.64   315.8 1639.05   331.6 1644.97   335.6 1645.63   371.8  1646.4
   403.9 1646.12   407.9  1646.5   411.9 1647.79   420.9 1651.85     433 1656.42
#Mann= 4 ,-1,0
       0      .1       0      50     .05       0  173.73    .045       0
   186.7     .05       0
#XS Ineff= 2 , 0
                          206.03         1640.22
Permanent Ineff=
       F       F
Bank Sta=173.73,186.7
XS Rating Curve= 0 ,0
Exp/Cntr(USF)=0,0
Exp/Cntr=0.3,0.1

Type RM Length L Ch R = 1 ,14485   ,257.8,259.7,258.1
XS GIS Cut Line= 2
 2202422.7964745696639.9344709362202712.11426057697038.010357741
#Sta/Elev= 30
       0  1653.2    16.2 1647.78    27.7 1642.89    36.2  1638.6    39.1 1637.62
    43.2  1636.7    53.4  1635.7    77.2 1634.37    90.8 1634.44   110.7 1633.97
   119.3 1634.21   206.5 1634.36   233.7 1633.75   273.9 1634.25     294 1633.99
   299.7  1633.1   302.6    1633   307.1 1634.11     314 1635.62   322.6 1635.96
   328.9 1636.73   376.5 1640.37   385.6 1640.74   414.2 1642.69   431.4 1643.53
   441.6  1643.7   454.3 1644.26   468.6 1644.43   478.6 1645.92   492.1 1646.72
#Mann= 4 ,-1,0
       0     .05       0     294    .045       0   307.1     .05       0
     460     .07       0
Bank Sta=294,307.1
XS Rating Curve= 0 ,0
Exp/Cntr(USF)=0,0
Exp/Cntr=0.3,0.1

Type RM Length L Ch R = 1 ,14225   ,241.9,242.6,241.9
XS GIS Cut Line= 2
2202237.49336749696780.4886873142202532.32208981697195.718886607
#Sta/Elev= 30
       0 1648.16    35.2 1642.82    48.3  1639.5      53 1638.68   123.5 1634.59
   157.8 1633.09   182.4 1632.62   197.1 1632.77   206.9 1633.27   239.5  1633.3
   315.1 1633.09   320.9 1632.72   324.6  1631.7   326.6 1631.46   329.5 1631.65
   334.4  1632.6   344.2  1635.2   349.2 1635.94   378.6 1637.27   389.7 1637.26
   412.9 1637.97   417.8 1638.94     427 1642.38   435.6 1646.94   438.5 1647.82
     450 1648.29     470 1648.04   471.8 1648.23   488.3 1652.81   509.3 1660.13
#Mann= 7 ,-1,0
       0     .05       0     160     .08       0     280     .05       0
   320.9    .045       0   334.4     .05       0     400     .07       0
     450     .06       0
#XS Ineff= 2 , 0
          206.64 1638.18
Permanent Ineff=
       F       F
Bank Sta=320.9,334.4
XS Rating Curve= 0 ,0
Exp/Cntr(USF)=0,0
Exp/Cntr=0.3,0.1

Type RM Length L Ch R = 1 ,13982   ,179.8,180.9,179.1
XS GIS Cut Line= 3
2202044.82288211696900.1257028052202291.18473017697269.734286175
2202326.09965647697323.823215839
#Sta/Elev= 30
       0 1654.19     8.9 1652.38    49.3 1646.97    85.4 1640.42   124.3 1636.54
   174.3 1633.56   251.2 1633.34   265.7 1634.69   277.2  1633.8   289.7 1632.33
   299.3 1630.82   303.2 1631.26   307.41632.328   311.8 1632.88     332 1633.33
   352.2 1635.75   366.6 1638.03   383.9 1641.43   400.3 1645.32   418.5  1647.5
   435.9 1651.26   447.4 1654.29   453.2 1655.26   464.8 1656.14   481.6 1655.63
   486.4 1656.05   491.1 1657.92   495.9 1660.63     505 1667.93   508.6 1669.89
#Mann= 9 ,-1,0
       0      .1       0     110     .05       0     130      .1       0
     250     .08       0   289.7    .045       0   307.4      .1       0
     370     .05       0  464.19     .07       0  484.19      .1       0
#XS Ineff= 2 , 0
          265.68  1638.8
Permanent Ineff=
       T       F
Bank Sta=289.7,307.4
XS Rating Curve= 0 ,0
Exp/Cntr(USF)=0,0
Exp/Cntr=0.3,0.1

Type RM Length L Ch R = 1 ,13802   ,332.7,351.2,341.6
XS GIS Cut Line= 2
2201827.19899611696949.8619154692202223.04340224697434.874084635
#Sta/Elev= 30
       0 1661.64    14.2 1657.61    31.5 1654.39      40 1651.96    52.2 1650.25
    91.2 1639.48    99.7 1638.12   182.2 1634.74     216 1635.48   231.5 1631.89
     239 1631.19   349.9 1632.41   355.6 1632.34   359.9  1631.3   365.7 1630.62
   370.9 1631.31   386.8 1632.72   406.4 1633.04   432.8  1635.2   479.3 1642.53
     492 1645.88     529 1653.31   541.2 1656.91   551.7 1662.38   577.4 1662.18
     583 1665.31   596.2 1675.77   603.2 1679.27   608.9 1680.72     626 1681.33
#Mann= 9 ,-1,0
       0      .1       0      80     .05       0     130      .1       0
     290     .08       0     330     .07       0   359.9    .045       0
   370.9     .07       0     440      .1       0     590     .06       0
Bank Sta=359.9,370.9
XS Rating Curve= 0 ,0
Exp/Cntr(USF)=0,0
Exp/Cntr=0.3,0.1

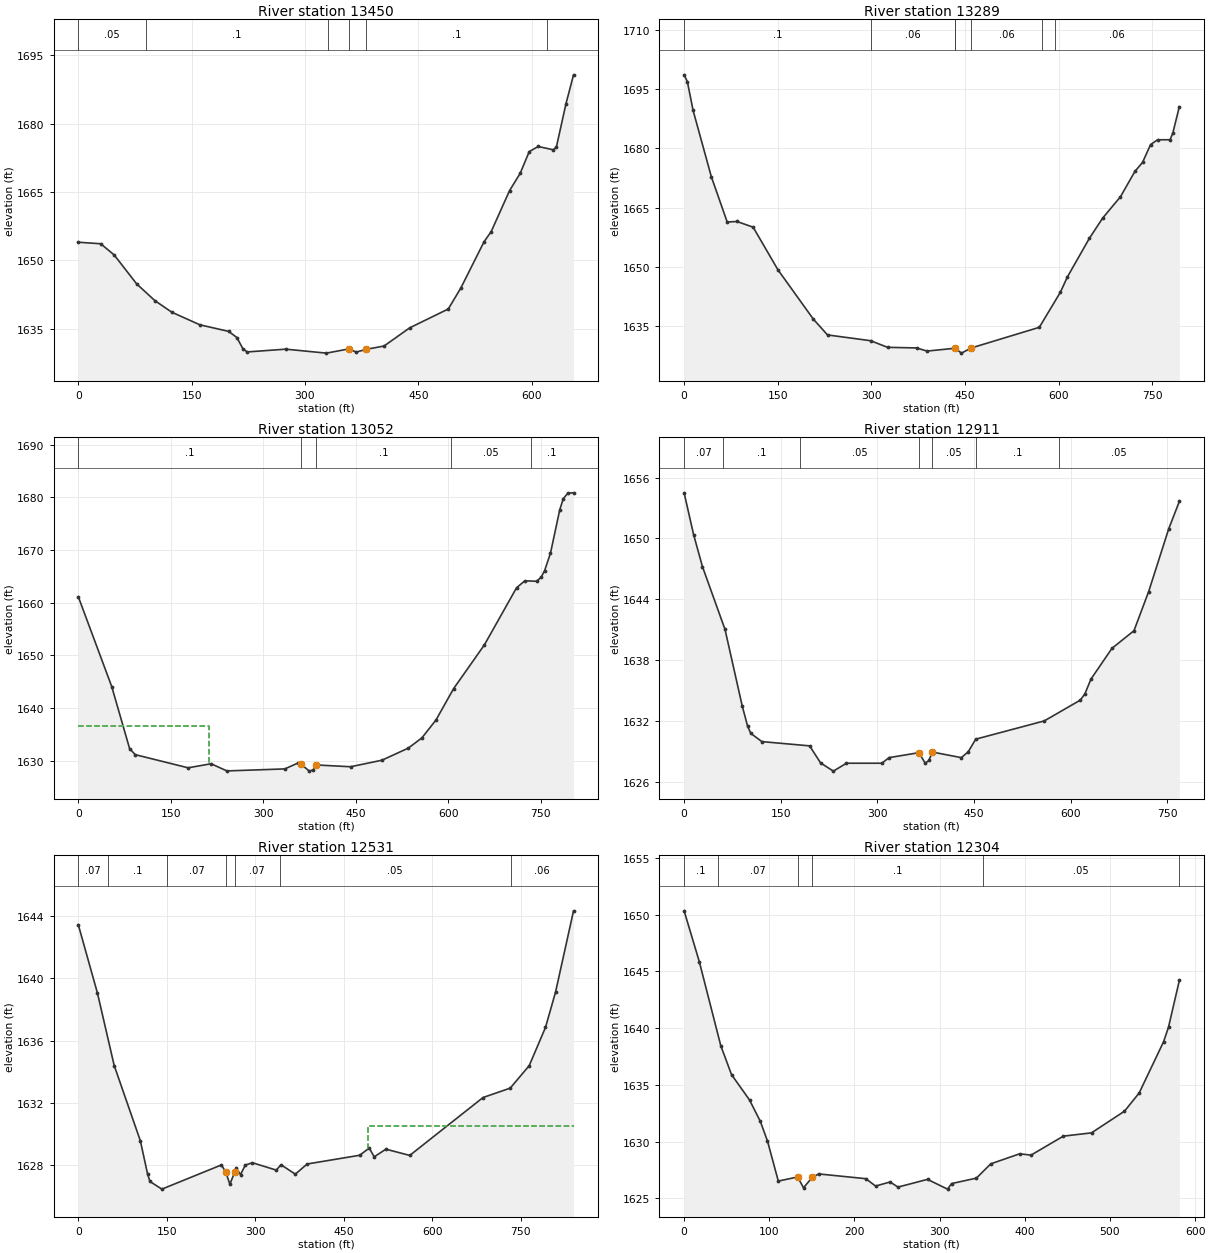
Type RM Length L Ch R = 1 ,13450   ,154.4,161,153.3
XS GIS Cut Line= 2
2201588.37291152697141.3210210632202027.44997122697628.009964712
#Sta/Elev= 30
       0 1653.98    29.6 1653.65    47.5 1651.19    77.3 1644.82   101.2 1641.18
   123.7 1638.62   160.9 1635.85   199.1  1634.4   209.9 1633.05   217.8 1630.62
   223.5 1629.89   274.6  1630.5   328.4 1629.63     358 1630.55   367.9 1629.86
   380.81630.445   404.8  1631.2   438.7 1635.19   489.7 1639.32   506.2 1643.89
   537.1  1654.1   546.4 1656.28   570.9 1665.34   584.9 1669.11   596.8 1673.86
   608.7 1675.01   628.5 1674.28   632.7  1674.8   645.5 1684.39   655.5 1690.74
#Mann= 6 ,-1,0
       0     .05       0      90      .1       0     330     .07       0
     358    .045       0   380.8      .1       0     620     .06       0
Bank Sta=358,380.8
XS Rating Curve= 0 ,0
Exp/Cntr(USF)=0,0
Exp/Cntr=0.3,0.1

Type RM Length L Ch R = 1 ,13289   ,239.2,237,233.5
XS GIS Cut Line= 4
2201347.62054612697255.9170672392201648.05664242697423.580823642
2201850.30094856697623.0735065662201959.00203502697747.394870104
#Sta/Elev= 30
       0 1698.67     5.2 1696.95    14.4 1689.64    43.6 1672.82      69 1661.33
    84.7 1661.46   110.6 1660.01   150.3  1649.2   207.1 1636.67   229.7 1632.68
   298.8 1631.21   325.9 1629.53   372.3 1629.38   389.2 1628.58   434.1  1629.3
   444.3 1628.06   460.2 1629.38     569 1634.61   602.7  1643.5     614  1647.4
   649.2 1657.19   670.6 1662.35     699 1667.74   722.1 1674.16   734.3 1676.43
   747.2 1680.97   758.4 1682.19   778.4  1682.2   782.9 1683.92   793.3 1690.59
#Mann= 7 ,-1,0
       0      .1       0     300     .06       0  434.05      .1       0
   434.1    .045       0   460.2     .06       0  574.05      .1       0
  594.05     .06       0
Bank Sta=434.1,460.2
XS Rating Curve= 0 ,0
Exp/Cntr(USF)=0,0
Exp/Cntr=0.3,0.1

Type RM Length L Ch R = 1 ,13052   ,137.8,141.8,143.3
XS GIS Cut Line= 5
2201222.93085605697468.9826066522201381.14919078697554.282926247
2201509.09967018697617.570260141 2201621.9162219697702.870579736
2201862.68325301697942.261799245
#Sta/Elev= 30
       0 1661.12    54.2 1644.08    83.2 1632.31    92.3 1631.15   178.2 1628.65
   215.4 1629.42   241.1 1628.06   335.1 1628.44   355.8 1629.53   361.6 1629.31
   374.9 1628.02   381.5 1628.28   385.91629.193   441.7 1628.85   492.6 1630.09
   535.3 1632.38   557.4 1634.32   580.3 1637.72     609 1643.69   658.9 1651.99
   711.1 1662.83   724.5 1664.14   743.5 1664.06   750.9  1664.8   756.5 1666.05
   766.1 1669.39   781.1  1677.6   786.8 1679.71   794.3 1680.79   803.5 1680.84
#Mann= 5 ,-1,0
       0      .1       0   361.6    .045       0   385.9      .1       0
  603.93     .05       0  733.93      .1       0
#XS Ineff= 2 , 0
          212.79  1636.5
Permanent Ineff=
       F       F
Bank Sta=361.6,385.9
XS Rating Curve= 0 ,0
Exp/Cntr(USF)=0,0
Exp/Cntr=0.3,0.1

Type RM Length L Ch R = 1 ,12911   ,362.3,379.5,389
XS GIS Cut Line= 4
2201177.32473954697511.1247352752201323.31210909697620.336660589
2201572.93936695697865.5062888452201742.78646633698029.963098187
#Sta/Elev= 30
       0  1654.5    14.9 1650.34    28.5 1647.22    63.5 1641.03    90.2 1633.49
    98.5 1631.51   103.5 1630.79   120.7 1629.98   194.8 1629.56   211.8 1627.88
   231.6 1627.07     252 1627.85   306.9 1627.85   318.1  1628.4   364.5 1628.89
   374.2 1627.85   379.8 1628.12   385.4 1628.95   430.2  1628.4   440.9 1628.97
   452.6 1630.22     559 1632.02   614.7 1634.06     622 1634.68   631.4 1636.14
     664 1639.17   698.2 1640.91     721 1644.77   752.1 1650.95   768.6 1653.65
#Mann= 7 ,-1,0
       0     .07       0      60      .1       0     180     .05       0
   364.5    .045       0   385.4     .05       0  452.32      .1       0
  582.21     .05       0
Bank Sta=364.5,385.4
XS Rating Curve= 0 ,0
Exp/Cntr(USF)=0,0
Exp/Cntr=0.3,0.1

Type RM Length L Ch R = 1 ,12531   ,222.6,227.6,226.6
XS GIS Cut Line= 4
2201174.01752623  697556.99004792201163.98785962697627.197714173
2201101.58104515698075.1894894412200826.85162033698231.018533485
#Sta/Elev= 30
       0 1643.42    32.5 1639.03    60.8  1634.4   105.2 1629.57   117.3 1627.46
   121.4 1626.97   141.6 1626.48   242.5 1628.03   249.8 1627.58   256.8 1626.79
     265 1627.57   267.5 1627.85   274.9 1627.41   282.9 1628.02     295 1628.17
   335.4  1627.7   343.5 1628.04   367.7 1627.44   387.8 1628.09   476.8 1628.65
   492.9 1629.11   501.4 1628.55   521.2 1629.04   561.6 1628.64   685.8 1632.35
   731.8 1632.95     764 1634.39   791.6 1636.84   808.6  1639.1   839.1 1644.31
#Mann= 7 ,-1,0
       0     .07       0      50      .1       0  150.92     .07       0
   249.8    .045       0     265     .07       0  340.92     .05       0
  733.24     .06       0
#XS Ineff= 2 , 0
                          491.08         1630.51
Permanent Ineff=
       F       F
Bank Sta=249.8,265
XS Rating Curve= 0 ,0
Exp/Cntr(USF)=0,0
Exp/Cntr=0.3,0.1

Type RM Length L Ch R = 1 ,12304   ,517.8,526.6,497.6
XS GIS Cut Line= 4
2200997.56344764697568.2148713512200978.87817875697625.895484028
2200868.39137137697948.4194732212200764.78424728698095.551782872
#Sta/Elev= 30
       0 1650.34    17.8 1645.87    43.1 1638.44    55.7  1635.9    76.8 1633.67
    89.5 1631.78    97.9 1630.05   110.6 1626.52   133.31626.881   140.2 1625.93
   150.4 1626.84     158 1627.15   213.4 1626.73   224.8 1626.08   241.8 1626.44
   251.2 1625.99   285.8 1626.67   309.3 1625.81   314.1  1626.3   343.2 1626.78
   360.1 1628.04   393.9 1628.92   407.4 1628.81   445.3 1630.48   478.4 1630.77
   517.1 1632.68   534.3 1634.28     563  1638.8   568.8 1640.09   581.5  1644.2
#Mann= 6 ,-1,0
       0      .1       0      40     .07       0   133.3    .045       0
   150.4      .1       0  350.63     .05       0  581.51     .06       0
Bank Sta=133.3,150.4
XS Rating Curve= 0 ,0
Exp/Cntr(USF)=0,0
Exp/Cntr=0.3,0.1

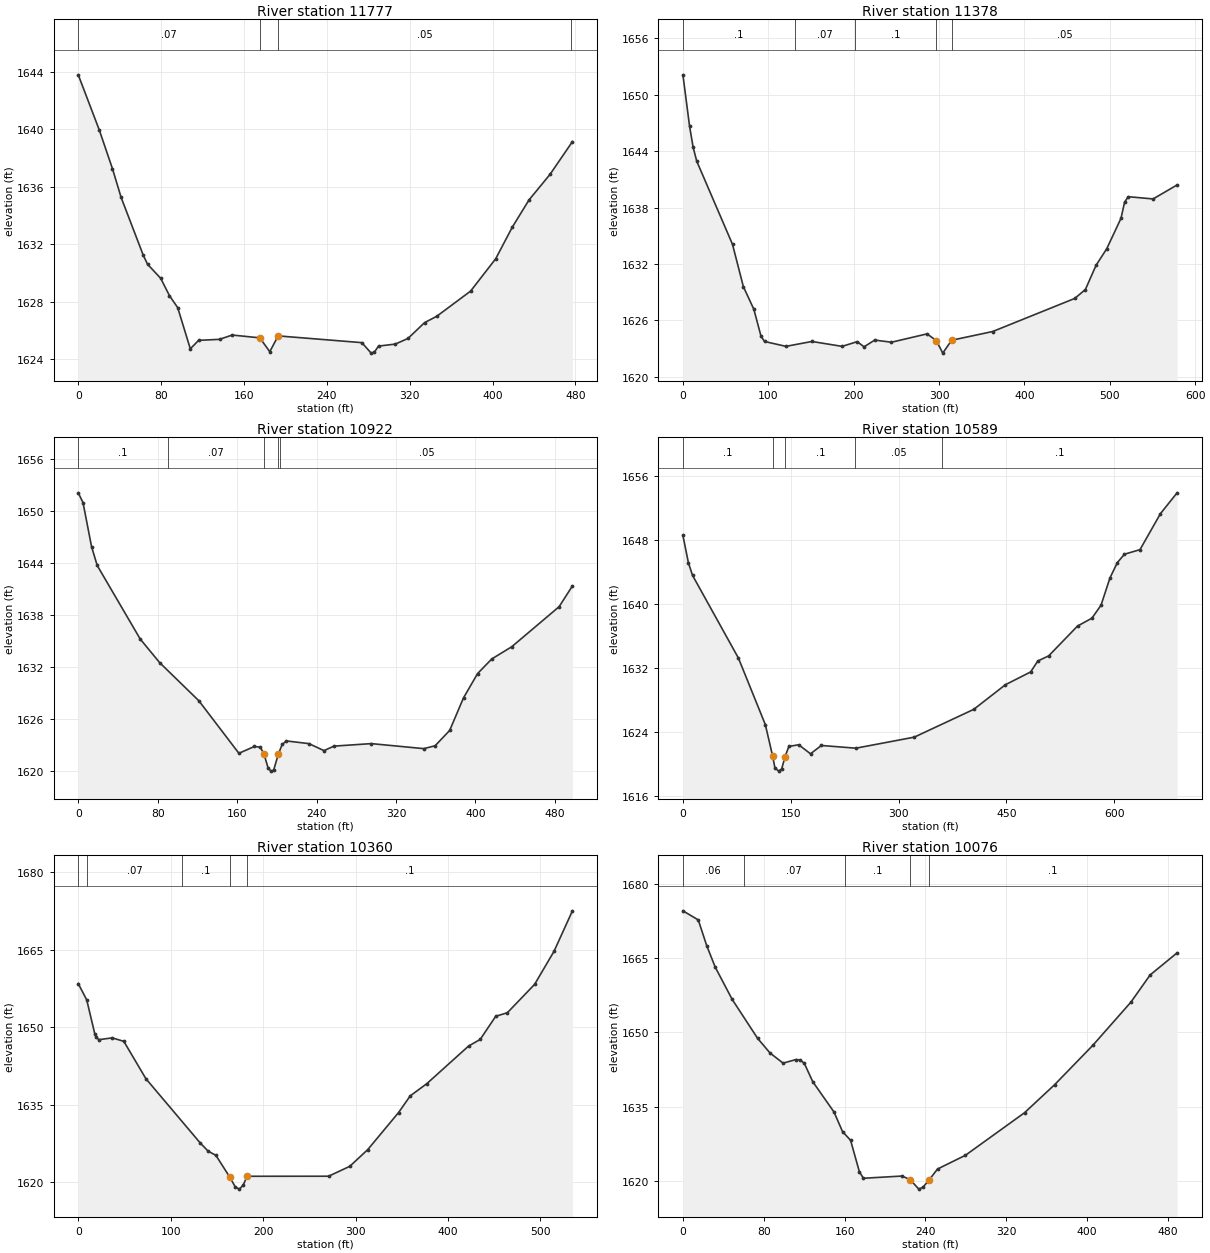
Type RM Length L Ch R = 1 ,11777   ,395.3,399.3,397.9
XS GIS Cut Line= 3
 2200688.8563767697530.1116726062200660.42227186697610.539569155
2200606.32066306 697998.61738154
#Sta/Elev= 30
       0  1643.8    20.2 1639.98      33 1637.27    41.4 1635.26    62.7 1631.25
    66.9 1630.61    79.6 1629.63      88 1628.43      96 1627.59   108.2 1624.72
   116.2 1625.31   136.4 1625.38   148.6 1625.68   175.31625.484   184.9 1624.52
     193 1625.62   273.8 1625.15   282.8 1624.42   285.9 1624.49   289.9 1624.91
   306.1 1625.05   318.3 1625.44   334.3 1626.54   346.2 1626.99   378.8 1628.74
     403 1630.99   419.1  1633.2   435.2 1635.09   455.5 1636.87   477.1 1639.15
#Mann= 4 ,-1,0
       0     .07       0   175.3    .045       0     193     .05       0
  475.31     .06       0
Bank Sta=175.3,193
XS Rating Curve= 0 ,0
Exp/Cntr(USF)=0,0
Exp/Cntr=0.3,0.1

Type RM Length L Ch R = 1 ,11378   ,440.5,456,449
XS GIS Cut Line= 3
2200369.40381813 697405.78058208 2200356.7664382697445.498061858
2200202.40986906697960.019958975
#Sta/Elev= 30
       0 1652.13     7.8 1646.67      12 1644.41    16.2 1642.94    58.1 1634.09
    70.8 1629.59    83.1 1627.18    91.5 1624.31    95.6 1623.75   120.7 1623.23
   151.1 1623.75   186.5 1623.23   204.2 1623.73   212.2 1623.18   224.7  1623.9
   244.3 1623.67     286 1624.56   296.9 1623.84   304.4 1622.51   314.8 1623.88
   362.9 1624.81     459 1628.33   471.5 1629.28     484 1631.86   496.5 1633.62
   513.2 1636.86   517.4 1638.57   521.6 1639.16   550.8 1638.92   578.9 1640.41
#Mann= 5 ,-1,0
       0      .1       0  131.68     .07       0  201.68      .1       0
   296.9    .045       0   314.8     .05       0
Bank Sta=296.9,314.8
XS Rating Curve= 0 ,0
Exp/Cntr(USF)=0,0
Exp/Cntr=0.3,0.1

Type RM Length L Ch R = 1 ,10922   ,322.3,332.8,331.9
XS GIS Cut Line= 3
2200183.02764265697337.3923752552200124.62163218697423.057859136
2199884.96274852697735.833012384
#Sta/Elev= 30
       0 1652.13     4.8    1651    13.4 1645.91    19.1 1643.73    62.4 1635.23
      82  1632.5   121.5 1628.09   161.8 1622.02   177.4 1622.81   183.3 1622.73
     187 1621.97   191.1 1620.36     194 1619.96   196.8 1620.08  201.65 1621.97
   205.4 1623.04   209.6 1623.45   232.3 1623.14   247.5 1622.33   257.5 1622.85
   295.1 1623.14     348 1622.56   359.4 1622.89   374.1 1624.67     388 1628.43
   402.2 1631.24   416.5 1632.93   436.5 1634.33   484.3 1638.97   497.7 1641.37
#Mann= 5 ,-1,0
       0      .1       0      90     .07       0     187    .045       0
  201.65     .07       0  203.68     .05       0
Bank Sta=187,201.65
XS Rating Curve= 0 ,0
Exp/Cntr(USF)=0,0
Exp/Cntr=0.3,0.1

Type RM Length L Ch R = 1 ,10589   ,220.2,228.6,231
XS GIS Cut Line= 2
2200025.66627233697259.8696938952199477.86060325697675.050288487
#Sta/Elev= 30
       0 1648.54     7.7  1645.1    13.4 1643.54    77.2  1633.2   114.7 1624.86
   124.8 1620.94     128 1619.46   133.3 1619.05   137.4 1619.33   142.11620.868
   147.4 1622.14   161.1 1622.35   177.5 1621.22   192.6 1622.26   240.6 1621.92
   321.8  1623.3   404.6 1626.78   448.6 1629.86   483.7 1631.46   493.7 1632.83
   508.8 1633.47   548.9  1637.2     569 1638.19   581.6 1639.81   594.1 1643.24
   604.4 1645.15   614.2 1646.19   635.8 1646.76   664.3 1651.27   687.4 1653.87
#Mann= 5 ,-1,0
       0      .1       0   124.8    .045       0   142.1      .1       0
     240     .05       0     360      .1       0
Bank Sta=124.8,142.1
XS Rating Curve= 0 ,0
Exp/Cntr(USF)=0,0
Exp/Cntr=0.3,0.1

Type RM Length L Ch R = 1 ,10360   ,277.8,284.1,279.1
XS GIS Cut Line= 3
2199944.72134657697133.7401409932199905.90455662697149.707896547
2199437.19621405697301.805718933
#Sta/Elev= 30
       0 1658.46     9.2 1655.28    17.9 1648.72    19.6 1648.05    22.2 1647.59
    36.8 1647.94    49.3 1647.27    73.2 1640.03   131.8 1627.62   140.5    1626
   148.9 1625.19   163.8 1621.01   169.9 1619.07   174.2 1618.64   178.4 1619.39
   182.6 1621.11   182.6 1621.13   270.9 1621.14   293.8 1623.06   313.2 1626.29
   346.6 1633.48   359.2  1636.7   377.2 1639.08   422.3 1646.35   434.9 1647.64
   451.7 1652.12   464.3 1652.81   493.8 1658.31   514.8 1664.71   534.7 1672.55
#Mann= 5 ,-1,0
       0     .06       0      10     .07       0  111.97      .1       0
   163.8    .045       0   182.6      .1       0
Bank Sta=163.8,182.6
XS Rating Curve= 0 ,0
Exp/Cntr(USF)=0,0
Exp/Cntr=0.3,0.1

Type RM Length L Ch R = 1 ,10076   ,315.5,323,317.9
XS GIS Cut Line= 2
2199890.66804595696931.4457080352199424.62783021697079.054678244
#Sta/Elev= 30
       0 1674.62    15.2 1672.78    23.6 1667.54      32 1663.21    48.8 1656.67
    73.9 1648.81    86.2 1645.84    99.1 1643.79   111.7  1644.5   115.9 1644.44
   120.1 1643.75   128.5 1640.02   149.5 1633.89   157.9 1629.94   165.9 1628.16
   174.6 1621.79   178.6 1620.48   216.9 1620.93     225 1620.17   233.4 1618.28
   237.6 1618.69   243.8  1620.2   251.9 1622.35   279.5 1625.13     338 1633.75
   367.7 1639.41   405.4 1647.36   443.2 1656.13   462.2 1661.63   488.9 1666.11
#Mann= 5 ,-1,0
       0     .06       0      60     .07       0     160      .1       0
     225    .045       0   243.8      .1       0
Bank Sta=225,243.8
XS Rating Curve= 0 ,0
Exp/Cntr(USF)=0,0
Exp/Cntr=0.3,0.1

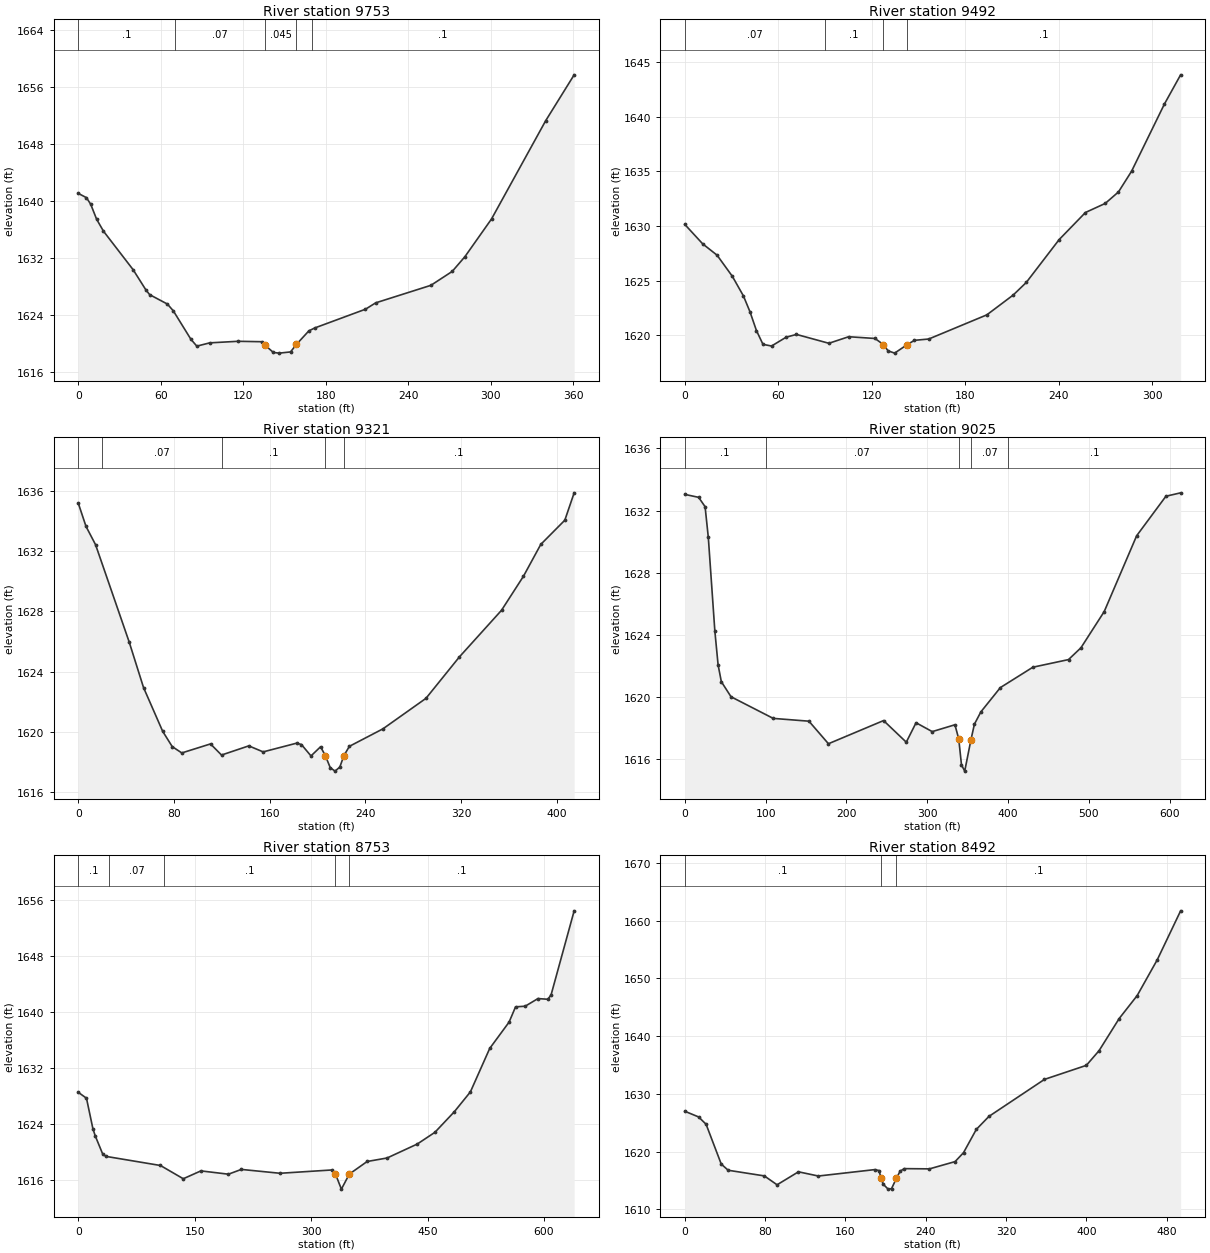
Type RM Length L Ch R = 1 ,9753    ,253.9,261.5,259.1
XS GIS Cut Line= 2
2199700.59471961696705.9639438662199364.09940483696835.848126471
#Sta/Elev= 30
       0 1641.02     5.9 1640.42       9  1639.5    13.3  1637.4    18.3 1635.72
    39.9 1630.31    49.2 1627.47    51.9 1626.82    64.8  1625.5    69.1 1624.55
    81.9 1620.56    86.2  1619.6    95.6 1620.06   116.2 1620.28   133.4 1620.22
   135.8 1619.74   141.9 1618.71   146.2 1618.62   154.4 1618.79   158.71619.855
   167.7 1621.74     172 1622.15   208.9 1624.78   216.3 1625.67   256.5 1628.13
     272 1630.08   281.2 1632.14   300.6 1637.44     340 1651.22   360.7 1657.65
#Mann= 5 ,-1,0
       0      .1       0      70     .07       0   135.8    .045       0
   158.7     .07       0     170      .1       0
Bank Sta=135.8,158.7
XS Rating Curve= 0 ,0
Exp/Cntr(USF)=0,0
Exp/Cntr=0.3,0.1

Type RM Length L Ch R = 1 ,9492    ,166.5,170.3,175.5
XS GIS Cut Line= 2
2199623.75045887696562.1283113592199322.34894756696664.491088786
#Sta/Elev= 30
       0 1630.15    11.5 1628.37    20.7 1627.34    30.5 1625.41    37.6 1623.62
    41.8 1622.18      46 1620.44    50.2 1619.18    55.7 1619.03    65.1 1619.84
    71.7 1620.09    92.5 1619.28   105.2 1619.88   122.1 1619.72  127.52 1619.16
   130.5 1618.59   134.7 1618.38  142.81 1619.16   147.4 1619.55   156.6 1619.67
   193.9 1621.88   210.8 1623.69   219.2 1624.84   240.3 1628.76   257.2 1631.24
   269.9 1632.07   278.4 1633.12   286.8 1635.01   307.9 1641.16   318.3 1643.83
#Mann= 4 ,-1,0
       0     .07       0      90      .1       0  127.52    .045       0
  142.81      .1       0
Bank Sta=127.52,142.81
XS Rating Curve= 0 ,0
Exp/Cntr(USF)=0,0
Exp/Cntr=0.3,0.1

Type RM Length L Ch R = 1 ,9321    ,296,295.9,292.7
XS GIS Cut Line= 2
2199658.61532025696451.8884036642199244.35297947 696438.36339824
#Sta/Elev= 30
       0 1635.19     6.4 1633.66    14.4 1632.44    42.5 1625.97    54.5 1622.94
    70.5 1620.03    78.5 1619.01    86.5 1618.59   110.5 1619.19   119.7 1618.45
   142.5 1619.06   154.5 1618.66   182.5 1619.24   186.5 1619.15   194.5 1618.39
   202.5    1619   206.5 1618.41   210.6 1617.61   214.6 1617.38   218.6 1617.65
     222 1618.41   226.6 1619.03   254.6 1620.19   290.6 1622.22   318.6 1624.98
   353.8 1628.08   372.1 1630.34   386.6 1632.46   406.7 1634.07   414.5 1635.89
#Mann= 5 ,-1,0
       0      .1       0      20     .07       0     120      .1       0
   206.5    .045       0     222      .1       0
Bank Sta=206.5,222
XS Rating Curve= 0 ,0
Exp/Cntr(USF)=0,0
Exp/Cntr=0.3,0.1

Type RM Length L Ch R = 1 ,9025    ,272.9,272.5,267.4
XS GIS Cut Line= 2
2199737.20517306696128.3327610732199126.05468647696180.257268059
#Sta/Elev= 30
       0 1633.04    17.1 1632.85    25.1 1632.25    29.1 1630.27    37.2 1624.24
    41.2 1622.08    45.2    1621    57.2 1620.03   109.4 1618.64   153.6 1618.46
   177.7 1617.01   245.9  1618.5     274 1617.11   286.1 1618.36   306.1 1617.79
   334.2 1618.23   338.91617.318   342.3 1615.65   346.3 1615.25     3541617.266
   358.3 1618.27   366.3 1619.06   390.4 1620.62   430.6 1621.93   474.7 1622.42
   490.1 1623.18   518.9 1625.51     559 1630.38   595.2 1632.92   613.4 1633.14
#Mann= 5 ,-1,0
       0      .1       0     100     .07       0   338.9    .045       0
     354     .07       0     400      .1       0
Bank Sta=338.9,354
XS Rating Curve= 0 ,0
Exp/Cntr(USF)=0,0
Exp/Cntr=0.3,0.1

Type RM Length L Ch R = 1 ,8753    ,260.9,260.7,259.7
XS GIS Cut Line= 2
2199642.31190847695816.4800951222199027.47606939695989.823997847
#Sta/Elev= 30
       0 1628.51    10.5 1627.67    18.8 1623.31    21.8  1622.3    31.3 1619.74
    35.5 1619.38   105.8 1618.08   135.2 1616.19   157.9 1617.31   193.4 1616.84
     210 1617.52   259.9 1616.97   326.4 1617.44  331.31 1616.85   338.9 1614.71
   349.2 1616.86   372.1 1618.65   397.8 1619.15   436.7 1621.14   459.4 1622.81
   484.3 1625.73   505.1 1628.57     530 1634.77     555 1638.53   563.3  1640.7
   575.7 1640.79   592.2 1641.88   604.8 1641.78     609 1642.38   638.8 1654.39
#Mann= 5 ,-1,0
       0      .1       0      40     .07       0     110      .1       0
  331.31    .045       0   349.2      .1       0
Bank Sta=331.31,349.2
XS Rating Curve= 0 ,0
Exp/Cntr(USF)=0,0
Exp/Cntr=0.3,0.1

Type RM Length L Ch R = 1 ,8492    ,310.8,320.8,316
XS GIS Cut Line= 3
2199428.73331752 695581.903579322199371.89854006695617.564616157
2198967.12740916695752.518951016
#Sta/Elev= 30
       0 1626.98    13.7    1626    21.2 1624.73    36.3 1617.83    43.2 1616.76
    79.2 1615.78    91.9 1614.24   113.2 1616.49     133 1615.76   189.1 1616.87
   193.3 1616.71   195.7 1615.34   197.5 1614.36   202.5 1613.49   205.9 1613.58
  210.71 1615.34   214.4  1616.6   218.6 1617.04   243.7    1617   269.2 1618.26
   277.6 1619.81   290.3 1623.83   302.9 1626.09   358.2  1632.5   399.9 1634.93
   412.6 1637.48   432.6 1643.04   450.5 1647.01   470.6 1653.24   493.8  1661.7
#Mann= 3 ,-1,0
       0      .1       0   195.7    .045       0  210.71      .1       0
Bank Sta=195.7,210.71
XS Rating Curve= 0 ,0
Exp/Cntr(USF)=0,0
Exp/Cntr=0.3,0.1