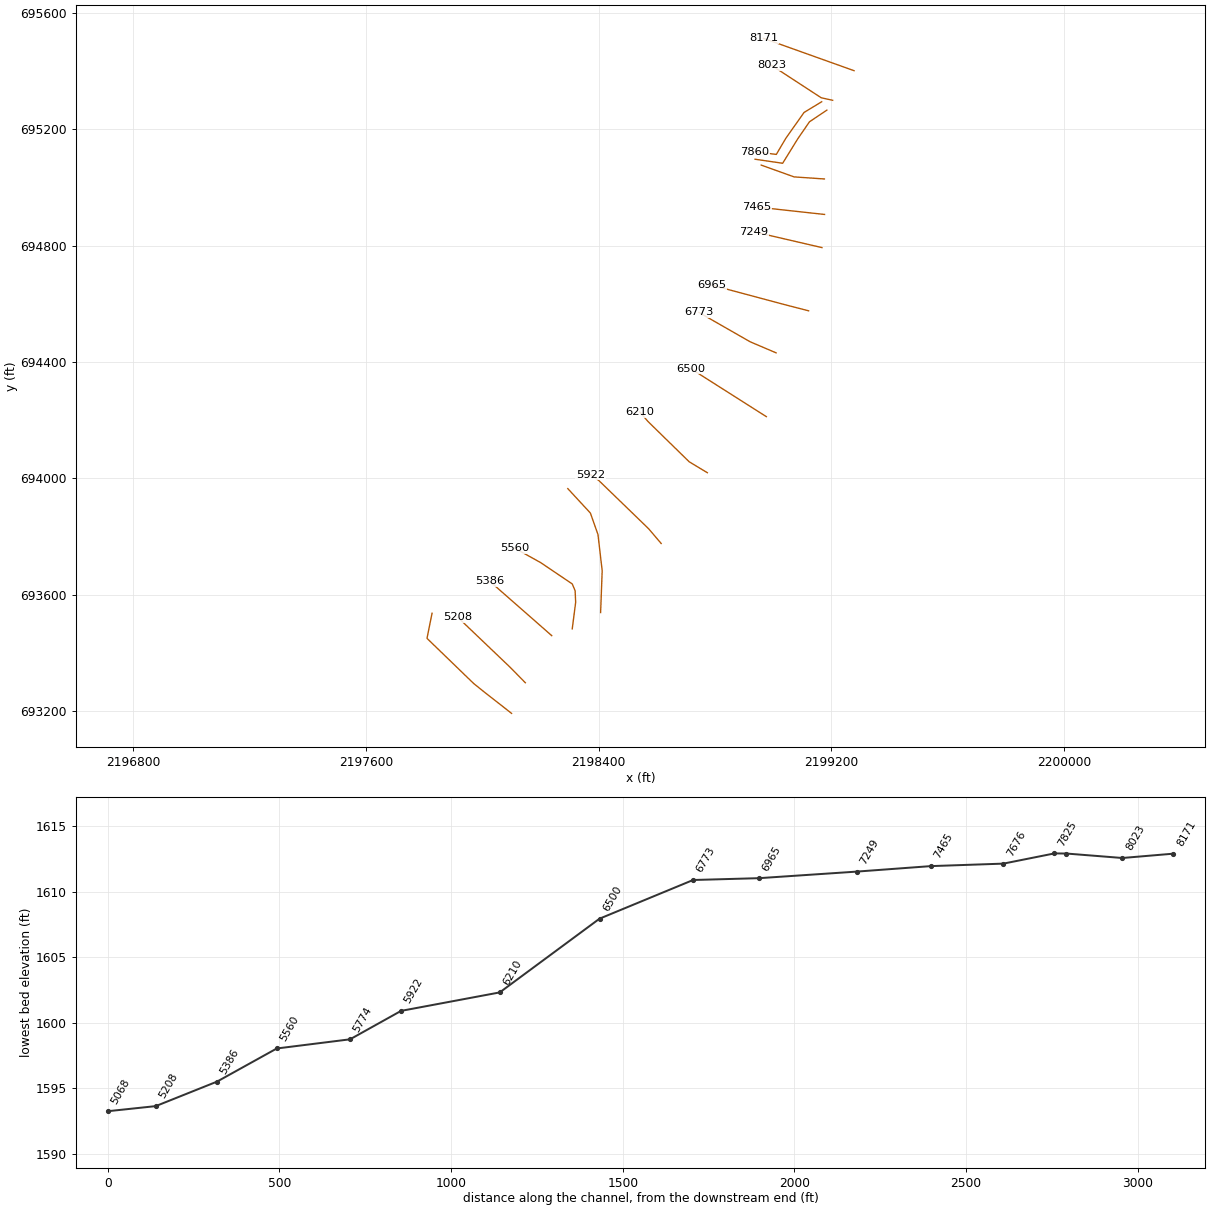
HEC-RAS study GRASSYRN.prj: GRASSYRN

--- GRASSYRN.g01 (geometry) --- (continued)

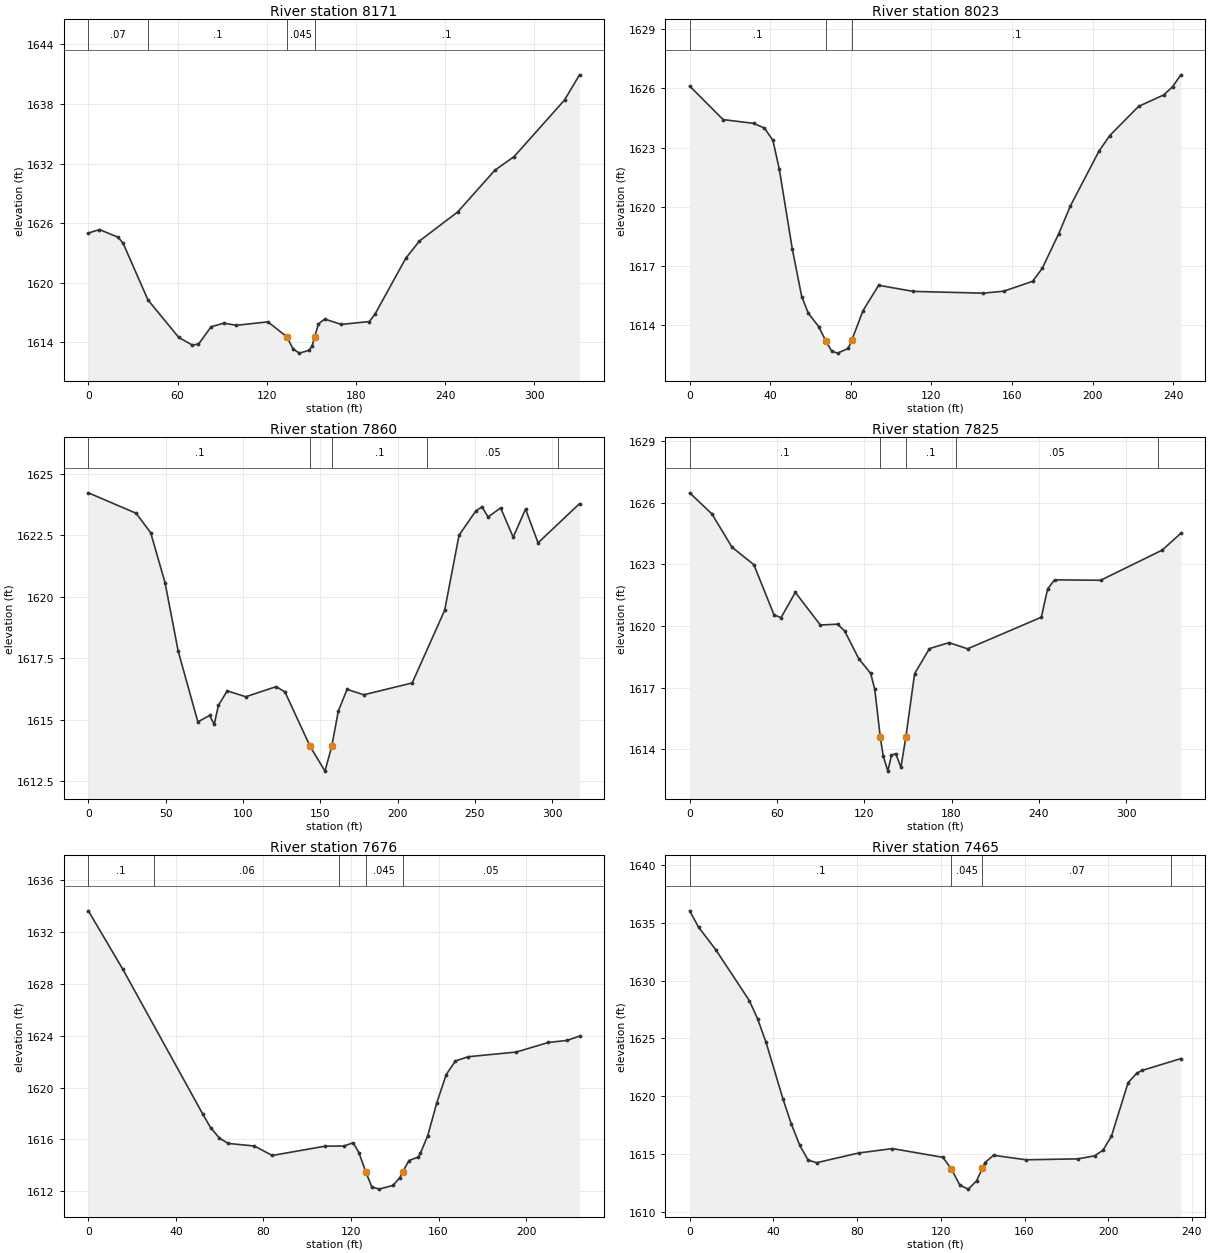
Type RM Length L Ch R = 1 ,8171    ,148.3,148.8,147.3
XS GIS Cut Line= 2
2199277.94252914695401.3078987532198966.68656949  695512.5177448
#Sta/Elev= 30
       0    1625     7.5 1625.35    20.1 1624.57    23.4 1623.97    40.1 1618.27
    60.7 1614.51    69.8 1613.73    74.1 1613.81    82.6 1615.56    91.1 1615.93
    99.6 1615.71   120.8 1616.06   133.6 1614.55   137.8 1613.32     142 1612.91
   148.4 1613.19   150.5  1613.6  152.22 1614.53   154.8 1615.84     159 1616.34
   170.3  1615.8   189.1 1616.09     193 1616.87   213.6 1622.46   222.8  1624.2
   248.5 1627.12   273.5 1631.32   286.5  1632.7   320.4 1638.39   330.5 1640.93
#Mann= 4 ,-1,0
       0     .07       0      40      .1       0   133.6    .045       0
  152.22      .1       0
Bank Sta=133.6,152.22
XS Rating Curve= 0 ,0
Exp/Cntr(USF)=0,0
Exp/Cntr=0.3,0.1

Type RM Length L Ch R = 1 ,8023    ,147,162.8,183.5
XS GIS Cut Line= 3
2199204.37763256695299.5101927432199164.87164034695308.322947868
2198994.53393883695419.420874872
#Sta/Elev= 30
       0 1626.12    16.6 1624.42    31.7 1624.23    37.1 1623.99    41.3 1623.37
    44.5  1621.9    50.9 1617.88    55.6 1615.45    58.9  1614.6      64 1613.93
    67.6 1613.19    70.5 1612.68    73.4 1612.58    78.7 1612.82    80.51613.245
      86 1614.73    93.8 1616.02     111 1615.71   145.7 1615.62   155.9 1615.72
   170.2 1616.22     175 1616.88   183.2 1618.64     189 1620.05   203.1 1622.81
   208.5 1623.61   222.8 1625.09   235.3 1625.67   239.7 1626.09   243.8 1626.69
#Mann= 3 ,-1,0
       0      .1       0    67.6    .045       0    80.5      .1       0
Bank Sta=67.6,80.5
XS Rating Curve= 0 ,0
Exp/Cntr(USF)=0,0
Exp/Cntr=0.3,0.1

Type RM Length L Ch R = 1 ,7860    ,34.5,34.9,35.8
XS GIS Cut Line= 5
2199166.59689545695294.5575824872199106.09431553695257.829977232
 2199043.6562751695169.4768489352199010.60918358695113.510000377
2198937.58577165695123.104317273
#Sta/Elev= 30
       0 1624.22    30.9 1623.39    40.3  1622.6    49.6 1620.57    58.1 1617.79
    70.8 1614.92    78.4 1615.18    81.4 1614.82    84.1 1615.59    89.8 1616.18
   101.8 1615.94   121.4 1616.35   127.1 1616.14  143.45 1613.92     153 1612.92
   157.41613.927   161.6 1615.35   167.3 1616.24   178.1 1616.02   209.4  1616.5
   230.4 1619.45   239.7  1622.5   250.5 1623.48   254.5 1623.65   258.5 1623.24
   266.6 1623.61   274.7 1622.42   282.7 1623.56   290.8 1622.19   317.6 1623.78
#Mann= 5 ,-1,0
       0      .1       0  143.45    .045       0   157.4      .1       0
  218.97     .05       0  303.96      .1       0
Bank Sta=143.45,157.4
XS Rating Curve= 0 ,0
Exp/Cntr(USF)=0,0
Exp/Cntr=0.3,0.1

Type RM Length L Ch R = 1 ,7825    ,163.7,148.8,126.6
XS GIS Cut Line= 5
2199184.33709594695265.7132141332199124.65769206695225.701563231
2199084.16561311695166.8117609092199032.46290539695083.127996874
2198937.58577165695096.986454612
#Sta/Elev= 30
       0 1626.49    15.3 1625.46    29.1 1623.84    44.1 1622.99      58 1620.54
    62.8 1620.41    72.6 1621.64    89.8 1620.05   101.6 1620.09   106.5 1619.76
   116.2 1618.41   124.4 1617.69   127.2 1616.92  130.99 1614.59     133 1613.68
   136.2 1612.93   138.7 1613.71   141.6 1613.78   145.2 1613.12  148.56 1614.58
   154.6 1617.68   164.8  1618.9   178.2 1619.19     191 1618.89   241.7 1620.43
     246  1621.8   250.8 1622.25   282.5 1622.23   324.8  1623.7   337.6 1624.52
#Mann= 5 ,-1,0
       0      .1       0  130.99    .045       0  148.56      .1       0
  183.32     .05       0  321.69      .1       0
Bank Sta=130.99,148.56
XS Rating Curve= 0 ,0
Exp/Cntr(USF)=0,0
Exp/Cntr=0.3,0.1

Type RM Length L Ch R = 1 ,7676    ,205.4,211.4,210.1
XS GIS Cut Line= 3
2199175.93314382695029.1638525232199071.80095267695036.270753927
 2198958.7795419695076.798781824
#Sta/Elev= 30
       0 1633.65    15.8 1629.12    52.3 1617.94    55.9 1616.89    59.9 1616.09
    63.9 1615.68    75.9 1615.48      84 1614.75   108.2 1615.47   116.7 1615.48
     121 1615.73   123.6 1614.97   126.7 1613.51   129.5 1612.32   132.9 1612.15
   139.2 1612.44   142.2 1613.01  143.64  1613.5   146.5 1614.36   150.7 1614.63
   151.7 1614.93     155 1616.25   159.2 1618.82   163.5    1621   167.7 1622.05
   173.6 1622.38   195.5 1622.74   210.2 1623.48   218.7 1623.64   224.4 1623.97
#Mann= 5 ,-1,0
       0      .1       0      30     .06       0  114.37     .05       0
   126.7    .045       0  143.64     .05       0
Bank Sta=126.7,143.64
XS Rating Curve= 0 ,0
Exp/Cntr(USF)=0,0
Exp/Cntr=0.3,0.1

Type RM Length L Ch R = 1 ,7465    ,210.8,216.1,208.5
XS GIS Cut Line= 2
  2199176.484612694907.2135865372198943.14134923694932.679983236
#Sta/Elev= 30
       0 1636.05     4.3 1634.62    12.4  1632.7    28.5 1628.28    32.5 1626.68
    36.5 1624.66    44.6 1619.75    48.6 1617.58    52.6 1615.75    56.6 1614.47
    60.7 1614.25    80.8 1615.09    96.9 1615.47     121 1614.71     125 1613.71
   129.1 1612.31   133.1 1611.96   137.1 1612.68   139.9 1613.78   141.1 1614.26
   145.2 1614.89   160.7  1614.5   185.4 1614.58   193.5 1614.84   197.5 1615.33
   201.5 1616.53   209.5 1621.18   213.6 1621.99   216.1 1622.23   234.7 1623.26
#Mann= 4 ,-1,0
       0      .1       0     125    .045       0   139.9     .07       0
     230      .1       0
Bank Sta=125,139.9
XS Rating Curve= 0 ,0
Exp/Cntr(USF)=0,0
Exp/Cntr=0.3,0.1

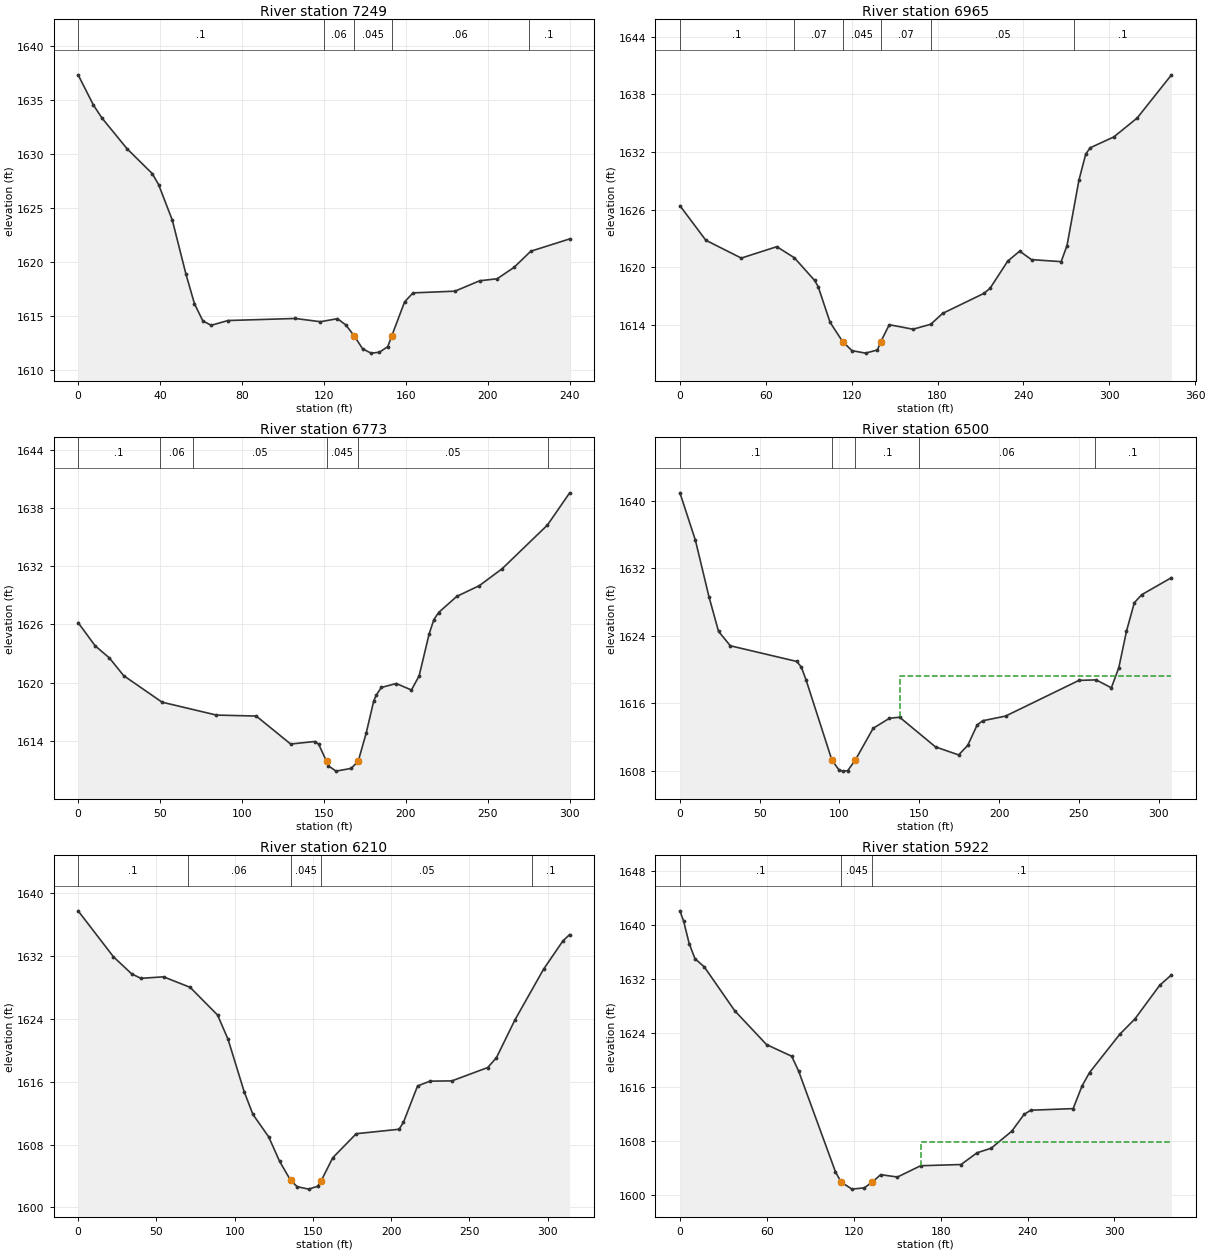
Type RM Length L Ch R = 1 ,7249    ,278.6,283.8,282.8
XS GIS Cut Line= 2
2199167.46945174694793.3156839692198933.67792305694847.475883666
#Sta/Elev= 30
       0 1637.32     7.5 1634.51    11.6 1633.33    23.9 1630.47    36.2 1628.17
    39.3 1627.15      46 1623.85    52.6 1618.89    56.8 1616.12    60.9 1614.52
      65 1614.12    73.2 1614.56     106 1614.75   118.3 1614.45   126.6 1614.73
   130.7 1614.15   134.8 1613.14   138.9 1611.94     143 1611.54   147.1 1611.62
   151.2 1612.15  153.13 1613.14   159.4 1616.29   163.5 1617.12     184 1617.28
     196 1618.24   204.6 1618.43   212.8 1619.48     221 1620.98     240 1622.12
#Mann= 5 ,-1,0
       0      .1       0     120     .06       0   134.8    .045       0
  153.13     .06       0     220      .1       0
Bank Sta=134.8,153.13
XS Rating Curve= 0 ,0
Exp/Cntr(USF)=0,0
Exp/Cntr=0.3,0.1

Type RM Length L Ch R = 1 ,6965    ,201.3,192.1,188.5
XS GIS Cut Line= 3
 2199121.6820612694575.9849448312199038.87976477 694597.35572341
2198789.62729907694664.069872369
#Sta/Elev= 30
       0  1626.4    18.1  1622.8    42.9 1620.94    67.7 1622.13      80 1620.97
    94.1 1618.62    96.6 1617.97   104.9 1614.26   113.7 1612.24   120.2  1611.3
   129.7 1611.04     138 1611.37  140.36 1612.23   146.3    1614   162.9 1613.53
   175.3 1614.05   183.6 1615.18   212.5 1617.27   216.7 1617.79   229.1 1620.63
   237.4 1621.66   245.7 1620.78   266.4 1620.57   270.5 1622.25   278.8 1629.04
   283.6 1631.79   286.8 1632.44   303.2 1633.56   319.5 1635.53   343.5 1640.03
#Mann= 6 ,-1,0
       0      .1       0      80     .07       0   113.7    .045       0
  140.36     .07       0  175.52     .05       0  275.52      .1       0
Bank Sta=113.7,140.36
XS Rating Curve= 0 ,0
Exp/Cntr(USF)=0,0
Exp/Cntr=0.3,0.1

Type RM Length L Ch R = 1 ,6773    ,270.9,272.4,271.7
XS GIS Cut Line= 3
2199009.77756031694431.6048091242198920.57571141694469.625269312
 2198744.3655017694570.525721347
#Sta/Elev= 30
       0 1626.19    10.4  1623.8    19.1 1622.55    27.8 1620.73    51.2    1618
    84.4 1616.67   108.7 1616.57   129.7 1613.69   144.4 1613.95   146.8 1613.67
   151.61611.914   152.7 1611.45   157.4  1610.9   166.6 1611.18  170.93 1611.92
   175.8 1614.81   180.4 1618.12   181.9 1618.71     185 1619.51   194.2 1619.92
   203.4 1619.25   208.1  1620.7   214.2 1625.01   217.1  1626.5     220 1627.23
   231.1 1628.89   244.9    1630   258.8 1631.74   286.4 1636.23     300 1639.55
#Mann= 6 ,-1,0
       0      .1       0      50     .06       0      70     .05       0
   151.6    .045       0  170.93     .05       0  286.97      .1       0
Bank Sta=151.6,170.93
XS Rating Curve= 0 ,0
Exp/Cntr(USF)=0,0
Exp/Cntr=0.3,0.1

Type RM Length L Ch R = 1 ,6500    ,291.3,290.7,287.1
XS GIS Cut Line= 2
2198976.38951227 694212.205500982198716.39536923694377.440958629
#Sta/Elev= 30
       0 1640.92     9.7 1635.31    18.2 1628.62    24.2 1624.51    31.6  1622.8
    73.3 1620.94    76.1 1620.27    79.1 1618.74    95.21609.289    99.8 1608.06
   102.3 1607.95   105.2 1608.01  110.02 1609.29   121.1 1613.02   131.3 1614.21
   137.7 1614.34   160.2 1610.82   174.7 1609.87   180.4    1611   186.3 1613.42
   189.8 1613.92   204.1 1614.47   250.1  1618.7   260.9 1618.76   270.4 1617.82
   275.1 1620.22   279.9 1624.53   284.8  1627.9   289.4 1628.85   308.1 1630.87
#Mann= 5 ,-1,0
       0      .1       0    95.2    .045       0  110.02      .1       0
     150     .06       0     260      .1       0
#XS Ineff= 2 , 0
                          137.76         1619.18
Permanent Ineff=
       F       F
Bank Sta=95.2,110.02
XS Rating Curve= 0 ,0
Exp/Cntr(USF)=0,0
Exp/Cntr=0.3,0.1

Type RM Length L Ch R = 1 ,6210    ,286.2,287.4,285.1
XS GIS Cut Line= 4
 2198773.5559489694019.5671579792198711.30450962694057.015032949
2198569.96408069694195.2114220862198541.23605709694228.267544005
#Sta/Elev= 30
       0 1637.78    22.6 1631.92    34.2 1629.75    40.1 1629.18    54.6 1629.37
    71.6 1628.03    89.1  1624.5    95.8 1621.41   106.1 1614.74   111.7 1611.84
   121.8 1608.97   128.7 1605.88   135.8 1603.43     140 1602.63   147.3 1602.32
     153 1602.68   155.3 1603.38   162.7 1606.32   177.7 1609.38   205.1 1609.95
   207.9 1610.85   216.9 1615.47   224.9 1616.08   238.8 1616.11   261.7 1617.81
   267.3 1619.07   279.1 1623.88   297.4 1630.34   309.8 1633.96   314.1 1634.76
#Mann= 5 ,-1,0
       0      .1       0      70     .06       0   135.8    .045       0
   155.3     .05       0  290.32      .1       0
Bank Sta=135.8,155.3
XS Rating Curve= 0 ,0
Exp/Cntr(USF)=0,0
Exp/Cntr=0.3,0.1

Type RM Length L Ch R = 1 ,5922    ,155.6,148.5,140.6
XS GIS Cut Line= 4
 2198614.8898549693776.2680130142198571.93360152693826.840130798
2198401.32897248693992.0287398752198372.44353264694012.790149759
#Sta/Elev= 30
       0 1642.07     2.6 1640.52     6.4 1637.23    10.4 1634.99    16.8 1633.79
    37.9 1627.28    59.8 1622.29    77.2 1620.56      82 1618.35   107.4 1603.47
  111.33 1601.94   118.8 1600.91   127.3  1601.1   132.8 1601.95   138.6 1603.05
   150.2  1602.7   166.2 1604.37   194.1 1604.55   205.2 1606.29   214.9 1606.96
   229.1 1609.47   237.6 1611.96   242.2 1612.58   271.5 1612.82   277.6 1616.15
   282.8 1618.15   303.8 1623.84   314.1 1626.07   331.3 1631.07   339.4  1632.6
#Mann= 3 ,-1,0
       0      .1       0  111.33    .045       0   132.8      .1       0
#XS Ineff= 2 , 0
                          166.17         1607.94
Permanent Ineff=
       F       F
Bank Sta=111.33,132.8
XS Rating Curve= 0 ,0
Exp/Cntr(USF)=0,0
Exp/Cntr=0.3,0.1

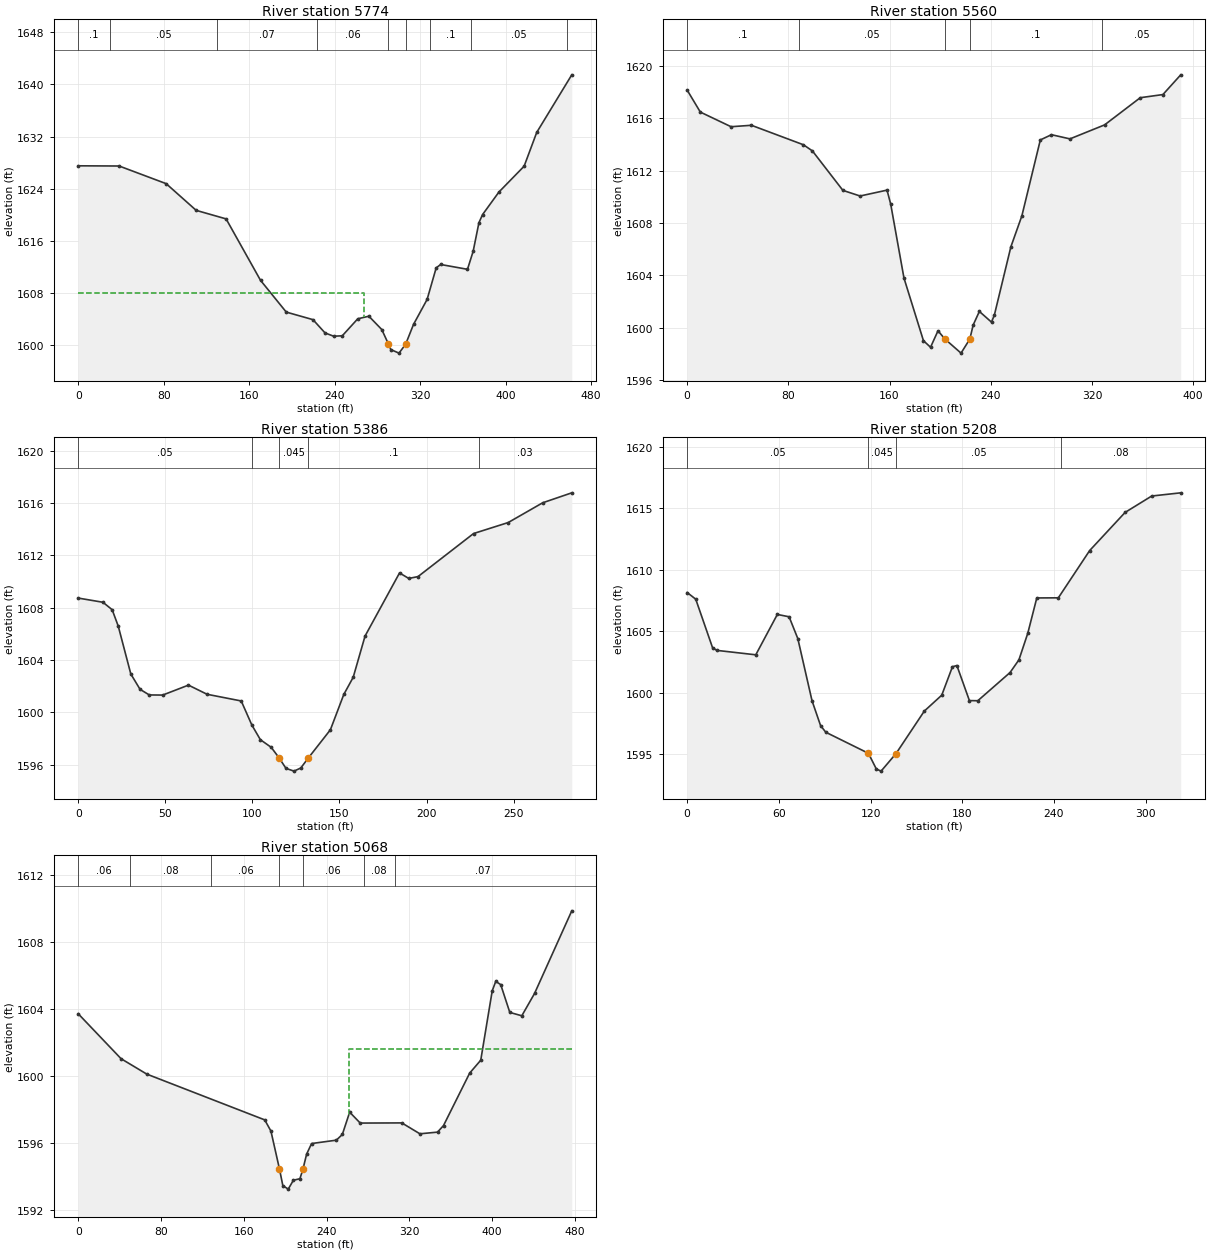
Type RM Length L Ch R = 1 ,5774    ,205.3,213.4,222
XS GIS Cut Line= 5
2198406.74499245693538.8884024062198412.16101241693682.412931605
 2198397.7182925693806.9813909092198371.54086264693881.000330495
2198293.91124308693964.948640026
#Sta/Elev= 30
       0  1627.5    38.3 1627.47    82.3 1624.76   110.4 1620.66   138.4 1619.35
   170.6 1609.92   194.7 1605.04   219.7 1603.88     231 1601.84     239 1601.34
   247.1  1601.4   261.6 1604.01     272 1604.41   284.1 1602.36   290.1 1600.21
   292.6 1599.28   300.2 1598.74   306.4  1600.1   313.8 1603.15   326.5 1606.98
     335 1611.83   339.2 1612.35   364.3 1611.61   369.6 1614.37     375 1618.76
   378.4 1620.01   393.7 1623.47   417.3 1627.44   429.1 1632.63   461.9 1641.47
#Mann= 9 ,-1,0
       0      .1       0      30     .05       0     130     .07       0
  223.63     .06       0   290.1    .045       0   306.4     .06       0
  329.03      .1       0  367.54     .05       0  457.54      .1       0
#XS Ineff= 2 , 0
          267.53 1607.99
Permanent Ineff=
       F       F
Bank Sta=290.1,306.4
XS Rating Curve= 0 ,0
Exp/Cntr(USF)=0,0
Exp/Cntr=0.3,0.1

Type RM Length L Ch R = 1 ,5560    ,175.9,174.1,172
XS GIS Cut Line= 6
2198309.25663299693482.9228627192198320.99134292 693574.09253221
2198319.18600293693613.8100119882198309.25663299693637.279431857
 2198200.9362336693710.3957014482198111.57190409693760.042551171
#Sta/Elev= 30
       0 1618.16    10.4 1616.48    34.7 1615.36    50.8 1615.47    91.9 1613.98
      99 1613.51   123.1 1610.49   136.7 1610.06     158 1610.51   160.9 1609.44
   171.4 1603.78   186.8 1598.99   192.4 1598.49   198.3 1599.75   203.71599.125
   216.5 1598.04  223.48 1599.12   226.1 1600.19     231 1601.23   240.6 1600.41
   242.9 1600.97   255.9 1606.17   264.6 1608.54   279.2 1614.35     288 1614.75
   302.6 1614.43     330  1615.5   358.2 1617.58   376.1 1617.82   390.2 1619.33
#Mann= 5 ,-1,0
       0      .1       0   88.34     .05       0   203.7    .045       0
  223.48      .1       0  327.96     .05       0
Bank Sta=203.7,223.48
XS Rating Curve= 0 ,0
Exp/Cntr(USF)=0,0
Exp/Cntr=0.3,0.1

Type RM Length L Ch R = 1 ,5386    ,179,178.4,177.5
XS GIS Cut Line= 2
2198238.84837338 693459.453442852198025.81825457693646.306131806
#Sta/Elev= 30
       0 1608.73    14.2 1608.41    19.5 1607.84      23 1606.58    30.2 1602.93
    35.5 1601.76    40.8 1601.33    48.5 1601.32    63.3 1602.08      74 1601.38
    93.6 1600.87    99.7 1599.03   104.6 1597.91   110.8 1597.33   115.3 1596.53
   119.3 1595.72   123.9 1595.51   127.8 1595.75   131.91596.476   144.8 1598.67
   152.5 1601.37   157.9 1602.68   164.7 1605.83   184.5 1610.65   189.8 1610.23
   195.1 1610.37     227 1613.66   246.9  1614.5   266.7 1616.01   283.4 1616.77
#Mann= 5 ,-1,0
       0     .05       0     100      .1       0   115.3    .045       0
   131.9      .1       0     230     .03       0
Bank Sta=115.3,131.9
XS Rating Curve= 0 ,0
Exp/Cntr(USF)=0,0
Exp/Cntr=0.3,0.1

Type RM Length L Ch R = 1 ,5208    ,136.3,140,141.5
XS GIS Cut Line= 3
 2198148.0826235693297.5826221462198095.72776379693350.840151848
2197916.09643479 693522.34745089
#Sta/Elev= 30
       0 1608.15     5.6 1607.61    16.6 1603.67    19.4 1603.45    44.9 1603.09
      59 1606.37    66.7 1606.18    72.4 1604.41    81.7 1599.36    87.3 1597.34
    90.7  1596.8   118.6 1595.09   123.8 1593.81   126.9 1593.64   136.7 1595.07
   155.2 1598.52   166.6 1599.81   173.6 1602.12   176.5 1602.22   184.7 1599.37
   190.2 1599.36   211.3 1601.65   217.1 1602.68   222.9 1604.84   228.8 1607.71
   242.9 1607.72   263.4 1611.56   286.6 1614.66     304 1615.99     323 1616.25
#Mann= 4 ,-1,0
       0     .05       0   118.6    .045       0   136.7     .05       0
  244.68     .08       0
Bank Sta=118.6,136.7
XS Rating Curve= 0 ,0
Exp/Cntr(USF)=0,0
Exp/Cntr=0.3,0.1

Type RM Length L Ch R = 1 ,5068    ,71.9,68.5,67.5
XS GIS Cut Line= 5
2198100.75834367  693192.35637492198007.31575113693265.399528222
2197970.46515126693295.0116174072197810.03953994693450.200174542
2197827.40806832693536.472145691
#Sta/Elev= 30
       0 1603.71    41.4 1601.03    66.3 1600.11   180.3 1597.38   186.3 1596.71
   194.51594.461   197.8 1593.46     203 1593.25     208 1593.78   214.3 1593.87
   217.21594.435   220.8 1595.34   225.6 1595.97   249.5 1596.17   255.3 1596.51
   262.4 1597.84   272.6 1597.19   312.8  1597.2   330.3 1596.55   347.3 1596.65
   353.1 1597.04   378.4 1600.17   389.1 1600.94   400.2 1605.08   403.6 1605.64
   408.4 1605.45   417.2 1603.79   428.8 1603.59   441.1 1604.92   477.1 1609.85
#Mann= 7 ,-1,0
       0     .06       0      50     .08       0   128.6     .06       0
   194.5    .045       0   217.2     .06       0  275.88     .08       0
  305.88     .07       0
#XS Ineff= 2 , 0
                          261.38         1601.58
Permanent Ineff=
       F       F
Bank Sta=194.5,217.2
XS Rating Curve= 0 ,0
Exp/Cntr(USF)=0,0
Exp/Cntr=0.3,0.1