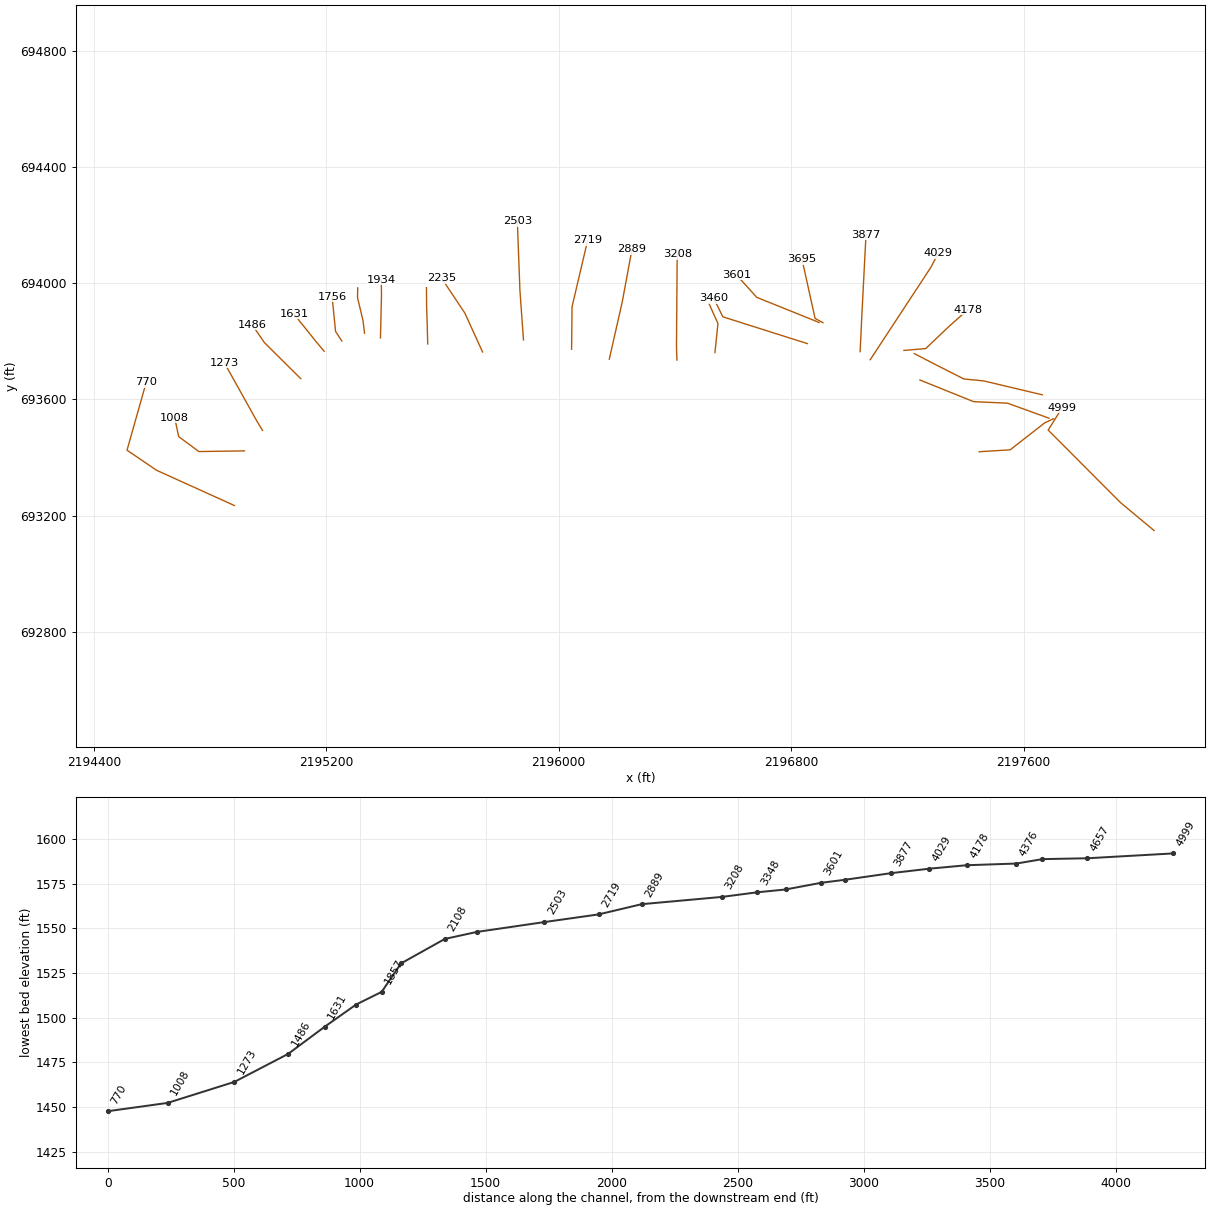
HEC-RAS study GRASSYRN.prj: GRASSYRN

--- GRASSYRN.g01 (geometry) --- (continued)

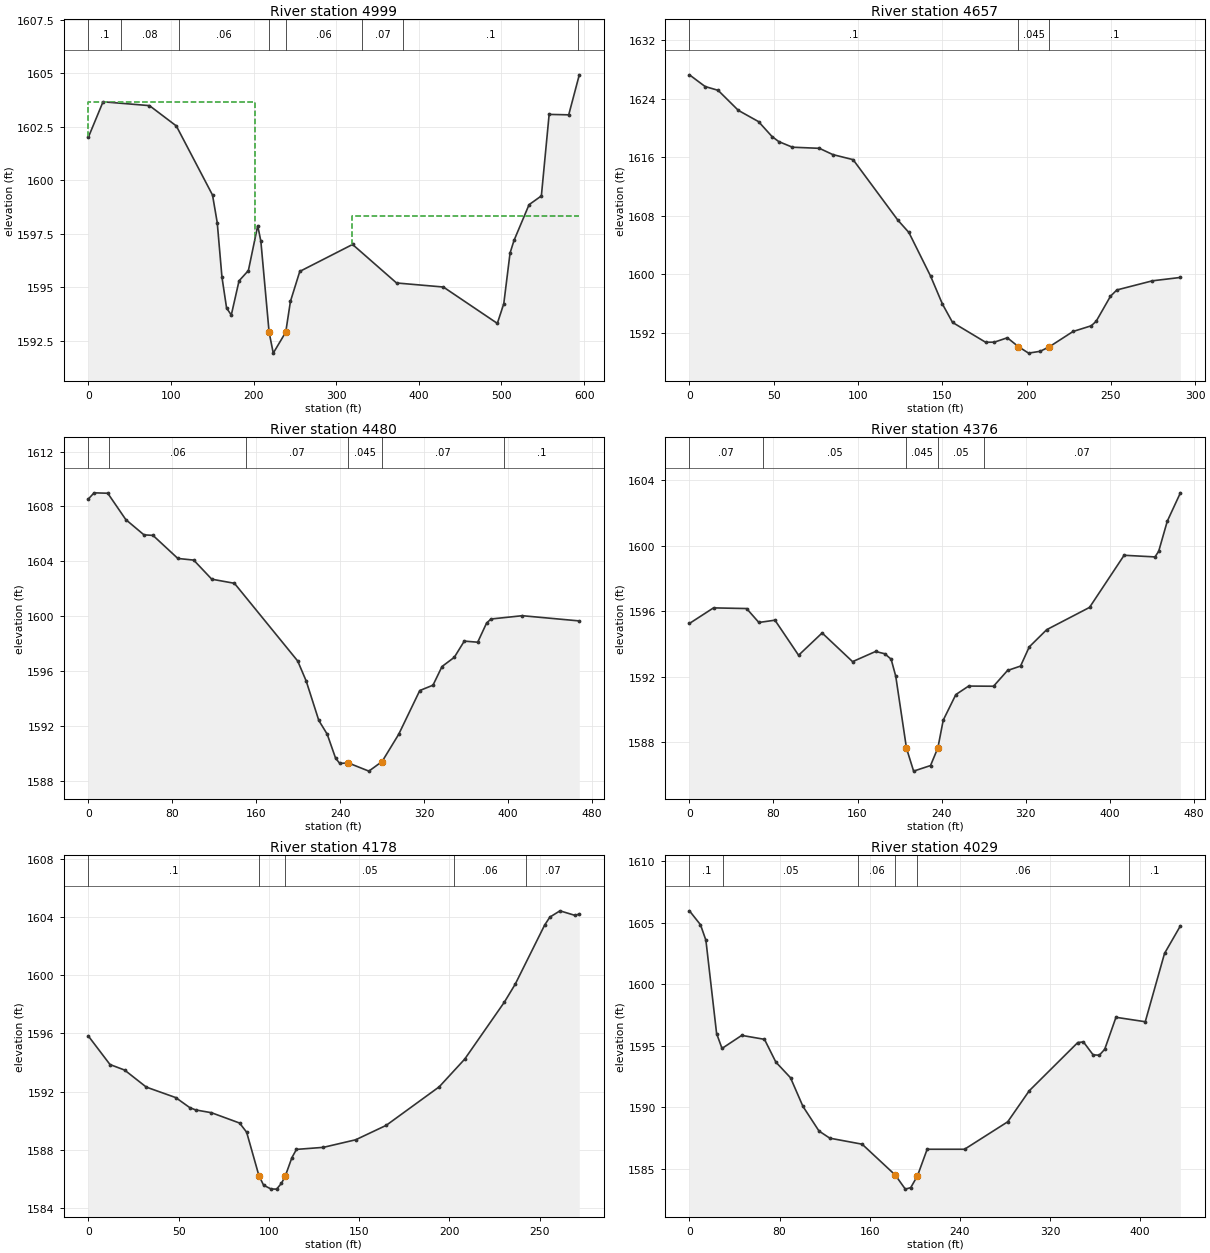
Type RM Length L Ch R = 1 ,4999    ,365.9,342.1,316
XS GIS Cut Line= 4
2198048.99262658693148.9830816432197932.95650496693245.658135433
2197684.52187501 693494.721055172197733.23431365693572.076367815
#Sta/Elev= 30
       0 1602.01    17.8 1603.67      74 1603.49   106.5 1602.54   150.3 1599.31
     156 1598.02   161.7 1595.48   167.3 1594.03     173  1593.7   182.4  1595.3
   193.7 1595.78     205 1597.88   208.8 1597.15  218.77  1592.9   223.8 1591.92
   238.9  1592.9   244.6 1594.34   255.9 1595.74   319.8    1597     373  1595.2
   429.7 1595.01     495 1593.31   502.8 1594.23   510.4  1596.6   515.2 1597.19
   533.4 1598.86   548.3 1599.27   557.7 1603.08   581.4 1603.06   594.2 1604.93
#Mann= 8 ,-1,0
       0      .1       0      40     .08       0     110     .06       0
  218.77    .045       0   238.9     .06       0  331.03     .07       0
  381.03      .1       0  592.82     .08       0
#XS Ineff= 2 , 0
        201.1405 1603.67  318.82         1598.32
Permanent Ineff=
       T       F
Bank Sta=218.77,238.9
XS Rating Curve= 0 ,0
Exp/Cntr(USF)=0,0
Exp/Cntr=0.3,0.1

Type RM Length L Ch R = 1 ,4657    ,194.3,177.7,148.8
XS GIS Cut Line= 4
2197447.22947978693420.2249842742197553.65427219693426.724208238
2197672.26510952 693519.338149722197703.13642335693533.961403638
#Sta/Elev= 30
       0 1627.26     9.3 1625.66      17 1625.14      29  1622.4      41 1620.86
      49 1618.82      53 1618.13    61.1 1617.36    77.1 1617.21    85.1 1616.35
    97.1 1615.66   123.6  1607.4   130.2  1605.7   143.1 1599.72   150.1 1595.91
   156.1  1593.4   175.7 1590.69   180.9  1590.7   188.6  1591.3   195.1  1590.1
   201.2  1589.2   208.1 1589.45   213.51590.064   227.6 1592.16   238.4 1592.94
   241.3 1593.55   249.8 1596.98   253.6 1597.84   274.7 1599.09   291.3 1599.55
#Mann= 3 ,-1,0
       0      .1       0   195.1    .045       0   213.5      .1       0
Bank Sta=195.1,213.5
XS Rating Curve= 0 ,0
Exp/Cntr(USF)=0,0
Exp/Cntr=0.3,0.1

Type RM Length L Ch R = 1 ,4480    ,106.2,103.2,118.3
XS GIS Cut Line= 4
2197243.06057142693667.0801537282197428.04473349693592.501558745
2197544.29960214693587.3834198732197687.24260879693535.721300571
#Sta/Elev= 30
       0 1608.54     5.5 1608.99    18.5 1608.96    35.7 1607.04      53 1605.93
    61.6 1605.89    85.3 1604.21   100.4 1604.09   117.6  1602.7   139.2  1602.4
   199.5 1596.74   207.6 1595.28   219.6 1592.41   227.6 1591.41   235.6 1589.66
   239.6 1589.28   247.6 1589.32   267.3 1588.72   279.9 1589.42   295.7  1591.4
   315.8 1594.59   328.4 1594.98     337 1596.34   348.7 1597.01   358.2 1598.19
     371 1598.11   379.5 1599.51   383.7  1599.8   413.5 1600.04   467.8 1599.66
#Mann= 6 ,-1,0
       0     .07       0      20     .06       0     150     .07       0
   247.6    .045       0   279.9     .07       0  395.82      .1       0
Bank Sta=247.6,279.9
XS Rating Curve= 0 ,0
Exp/Cntr(USF)=0,0
Exp/Cntr=0.3,0.1

Type RM Length L Ch R = 1 ,4376    ,173.3,197.9,210.7
XS GIS Cut Line= 5
 2197223.8603101693757.8781931152197304.10715005693716.418370491
2197394.67028767693670.5430822922197462.59441096693663.973246978
2197664.35067484693616.138498811
#Sta/Elev= 30
       0 1595.26    22.9 1596.21    54.4 1596.17    66.1 1595.32    81.4 1595.46
   103.9 1593.32   126.3 1594.68   155.3 1592.93   177.2 1593.55     186 1593.41
     192 1593.08   196.4 1592.04  206.621587.647   213.4 1586.25   229.5 1586.59
   236.5 1587.67   241.6 1589.36   253.6 1590.92   265.8 1591.44   289.5 1591.43
   302.8 1592.39   315.2 1592.66   323.5 1593.83   340.1 1594.88   380.9 1596.24
   413.8 1599.42   443.2 1599.32   446.7 1599.66   454.9  1601.5   467.4 1603.23
#Mann= 5 ,-1,0
       0     .07       0      70     .05       0  206.62    .045       0
   236.5     .05       0  280.08     .07       0
Bank Sta=206.62,236.5
XS Rating Curve= 0 ,0
Exp/Cntr(USF)=0,0
Exp/Cntr=0.3,0.1

Type RM Length L Ch R = 1 ,4178    ,146.1,149,152.8
XS GIS Cut Line= 4
2197188.19425843693768.8892068832197263.11586801693775.207896848
2197340.74548758693849.2268364342197407.54306721693908.803056101
#Sta/Elev= 30
       0 1595.82      12 1593.86    20.1 1593.48    32.1 1592.31    48.4 1591.59
    56.2  1590.9    59.5 1590.74    68.2 1590.55    83.8 1589.84    87.7 1589.21
    94.51586.228    97.1 1585.57   101.2 1585.31   104.3  1585.3     107  1585.7
   109.2 1586.23   112.8 1587.47   115.3 1588.03   130.2 1588.17   148.1 1588.69
     165 1589.68   194.4 1592.33   208.5 1594.23   230.5 1598.15   236.5 1599.38
   252.8 1603.44   255.7 1603.99   261.3 1604.42   269.8  1604.1     272 1604.21
#Mann= 5 ,-1,0
       0      .1       0    94.5    .045       0   109.2     .05       0
  202.45     .06       0  242.45     .07       0
Bank Sta=94.5,109.2
XS Rating Curve= 0 ,0
Exp/Cntr(USF)=0,0
Exp/Cntr=0.3,0.1

Type RM Length L Ch R = 1 ,4029    ,139.8,152.1,159.3
XS GIS Cut Line= 3
2197072.13799688693737.0128246942197280.65476571694054.752662917
2197306.83203283694104.022894744
#Sta/Elev= 30
       0 1605.96     9.8 1604.83    14.6 1603.57    24.1 1595.99    28.9 1594.78
    46.4 1595.84    66.6 1595.52    76.7 1593.67    89.7  1592.4   100.7 1590.08
     115 1588.07   124.6 1587.49   153.3    1587   182.71584.494   191.6 1583.35
   196.4 1583.47   202.4 1584.43     211 1586.59   244.2 1586.59   282.5 1588.82
   301.6 1591.34   344.7 1595.26   349.7 1595.31   358.3 1594.26   363.8 1594.23
   368.6 1594.71   378.6 1597.31   404.6 1596.95   421.7  1602.5   435.8 1604.74
#Mann= 6 ,-1,0
       0      .1       0      30     .05       0     150     .06       0
   182.7    .045       0   202.4     .06       0  390.05      .1       0
Bank Sta=182.7,202.4
XS Rating Curve= 0 ,0
Exp/Cntr(USF)=0,0
Exp/Cntr=0.3,0.1

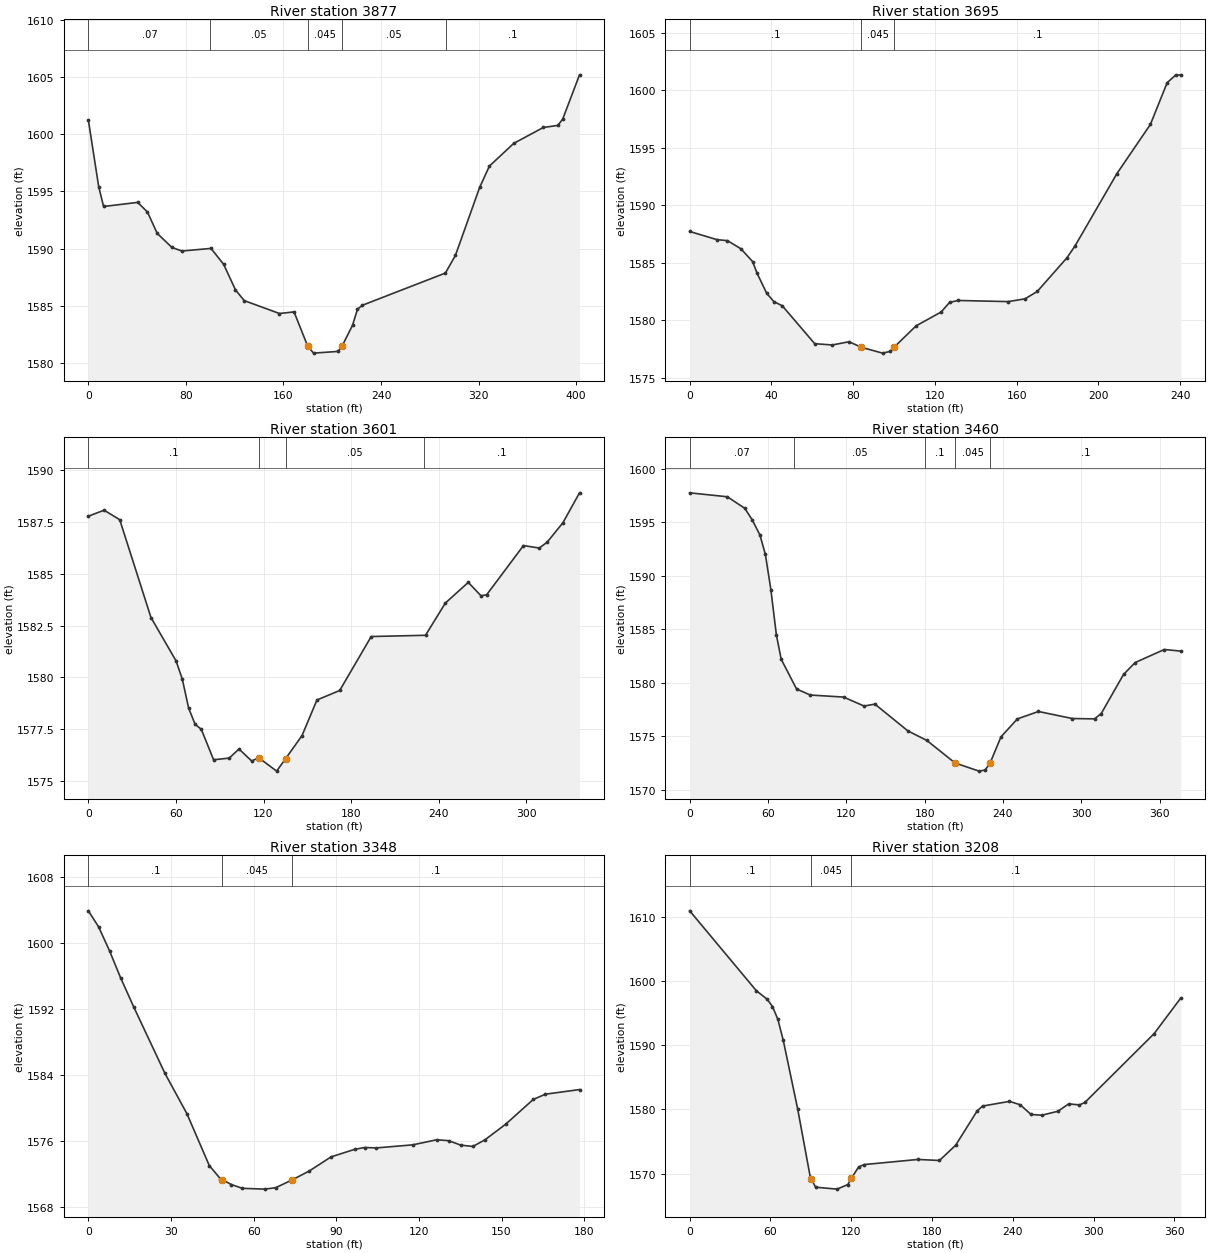
Type RM Length L Ch R = 1 ,3877    ,177.6,182.6,186.4
XS GIS Cut Line= 3
 2197037.2999499693764.7067401392197043.14925147693887.785793951
2197057.52878449 694167.00870349
#Sta/Elev= 30
       0 1601.25     8.5 1595.41    12.5 1593.68    40.5 1594.04    48.5 1593.19
    56.5 1591.32    68.5  1590.1    76.6 1589.78   100.6 1590.01     111 1588.61
   120.6 1586.39   127.8 1585.44   156.7 1584.31   168.7 1584.45  179.951581.432
   184.7 1580.84   204.7 1580.99   208.1 1581.46   216.7 1583.29   220.7 1584.68
   224.7 1585.03   292.8 1587.85     301 1589.39   320.9 1595.35   328.9 1597.22
   348.9 1599.21   373.1  1600.6     385 1600.78     389 1601.33   402.8 1605.21
#Mann= 5 ,-1,0
       0     .07       0     100     .05       0  179.95    .045       0
   208.1     .05       0  293.22      .1       0
Bank Sta=179.95,208.1
XS Rating Curve= 0 ,0
Exp/Cntr(USF)=0,0
Exp/Cntr=0.3,0.1

Type RM Length L Ch R = 1 ,3695    ,79.4,93.9,107.6
XS GIS Cut Line= 3
2196909.34647812693864.3885876822196882.29345837  693879.0118416
2196836.96137122694083.737396455
#Sta/Elev= 30
       0 1587.72    13.3 1587.01    18.5 1586.92    25.1 1586.21    30.8  1585.1
      33 1584.08    37.7 1582.34    41.2 1581.62    45.3 1581.26    61.2 1577.96
    69.8 1577.85      78 1578.13   84.021577.647    94.4 1577.14    98.1 1577.29
     1001577.646   110.8 1579.51   123.1 1580.72   127.2 1581.55   131.3 1581.72
   155.9 1581.62   164.1 1581.86   170.1  1582.5   184.6 1585.42   188.6 1586.46
   209.1 1592.75   225.5 1597.03   233.7 1600.66   237.8 1601.31   240.4 1601.34
#Mann= 3 ,-1,0
       0      .1       0   84.02    .045       0     100      .1       0
Bank Sta=84.02,100
XS Rating Curve= 0 ,0
Exp/Cntr(USF)=0,0
Exp/Cntr=0.3,0.1

Type RM Length L Ch R = 1 ,3601    ,137.2,140.6,144.9
XS GIS Cut Line= 3
2196895.94401487693865.1409079692196681.71334497693951.418106087
2196610.79056347 694029.65251455
#Sta/Elev= 30
       0 1587.79    10.8 1588.08    21.5 1587.62    42.9 1582.89    60.1 1580.79
    64.4  1579.9    68.7 1578.51    73.1 1577.73    77.4 1577.48    85.8 1576.01
    96.5 1576.09   103.2 1576.53   111.9 1575.95   116.7 1576.11     129 1575.46
   135.1 1576.06   146.4 1577.18   156.6  1578.9   172.2 1579.36   193.8 1581.97
     231 1582.03   244.6 1583.59   260.3 1584.59     269 1583.94   272.9 1583.99
   298.1 1586.37   308.9 1586.25   314.3 1586.53   325.1 1587.47   336.5 1588.92
#Mann= 4 ,-1,0
       0      .1       0   116.7    .045       0   135.1     .05       0
     230      .1       0
Bank Sta=116.7,135.1
XS Rating Curve= 0 ,0
Exp/Cntr(USF)=0,0
Exp/Cntr=0.3,0.1

Type RM Length L Ch R = 1 ,3460    ,138.1,112,89.3
XS GIS Cut Line= 3
 2196855.4863457693792.4308398762196564.64607332 693884.63857986
  2196533.368558693948.574695603
#Sta/Elev= 30
       0 1597.77    28.9  1597.4    42.2 1596.32    47.8 1595.26    53.8 1593.83
      58    1592    62.2 1588.71    66.4 1584.49    70.1  1582.2    81.9 1579.41
    92.4 1578.85   117.9 1578.66   133.6 1577.82   141.9    1578   167.1  1575.5
   181.7  1574.6  203.341572.491   221.7 1571.73   226.3 1571.83   230.1 1572.47
   238.5 1574.94   251.1 1576.62   267.2 1577.31   293.2 1576.65   310.2 1576.62
   315.3 1577.12   332.4 1580.78   341.3 1581.89   363.6 1583.11   376.3 1582.96
#Mann= 5 ,-1,0
       0     .07       0      80     .05       0     180      .1       0
  203.34    .045       0   230.1      .1       0
Bank Sta=203.34,230.1
XS Rating Curve= 0 ,0
Exp/Cntr(USF)=0,0
Exp/Cntr=0.3,0.1

Type RM Length L Ch R = 1 ,3348    ,138.4,140.4,142.4
XS GIS Cut Line= 3
2196537.64008683693761.5435255912196548.00194908693861.276449722
2196516.05287382693932.514252673
#Sta/Elev= 30
       0 1603.93     3.7    1602     7.7 1599.07    11.7 1595.81    16.5 1592.25
    27.8 1584.21    35.8  1579.3    43.9 1573.02    47.9 1571.43   48.69 1571.29
    51.9 1570.72    55.9 1570.26      64 1570.16      68 1570.33   73.981571.286
    80.1 1572.34    88.1 1574.07    96.7 1574.99   100.3 1575.21   104.5 1575.16
   117.7 1575.53   126.5 1576.15   130.8 1576.04   135.2  1575.5   139.6 1575.34
     144 1576.15   151.5 1578.04   161.5 1581.04   165.9 1581.68   178.3 1582.24
#Mann= 3 ,-1,0
       0      .1       0   48.69    .045       0   73.98      .1       0
Bank Sta=48.69,73.98
XS Rating Curve= 0 ,0
Exp/Cntr(USF)=0,0
Exp/Cntr=0.3,0.1

Type RM Length L Ch R = 1 ,3208    ,320.7,318.8,305.8
XS GIS Cut Line= 3
2196406.86591471693735.7173226292196405.24110872693780.399487379
2196407.67831771 694100.48626759
#Sta/Elev= 30
       0 1610.99    49.5 1598.53    57.5  1597.2    61.5 1596.06    65.5 1594.05
    69.5 1590.78    80.2 1580.08    89.5 1569.52   90.341569.173    93.5 1567.87
   109.5 1567.57   117.5 1568.29     1201569.234   125.5 1571.04   129.5  1571.4
   169.5  1572.2   185.5 1572.04   197.5 1574.41   213.5 1579.77   217.5 1580.53
   237.5 1581.26   245.5 1580.73   253.5 1579.22   261.5  1579.1   273.5 1579.72
   281.5 1580.87   289.5 1580.71   293.5 1581.09   344.9 1591.82   364.8  1597.4
#Mann= 3 ,-1,0
       0      .1       0   90.34    .045       0     120      .1       0
Bank Sta=90.34,120
XS Rating Curve= 0 ,0
Exp/Cntr(USF)=0,0
Exp/Cntr=0.3,0.1

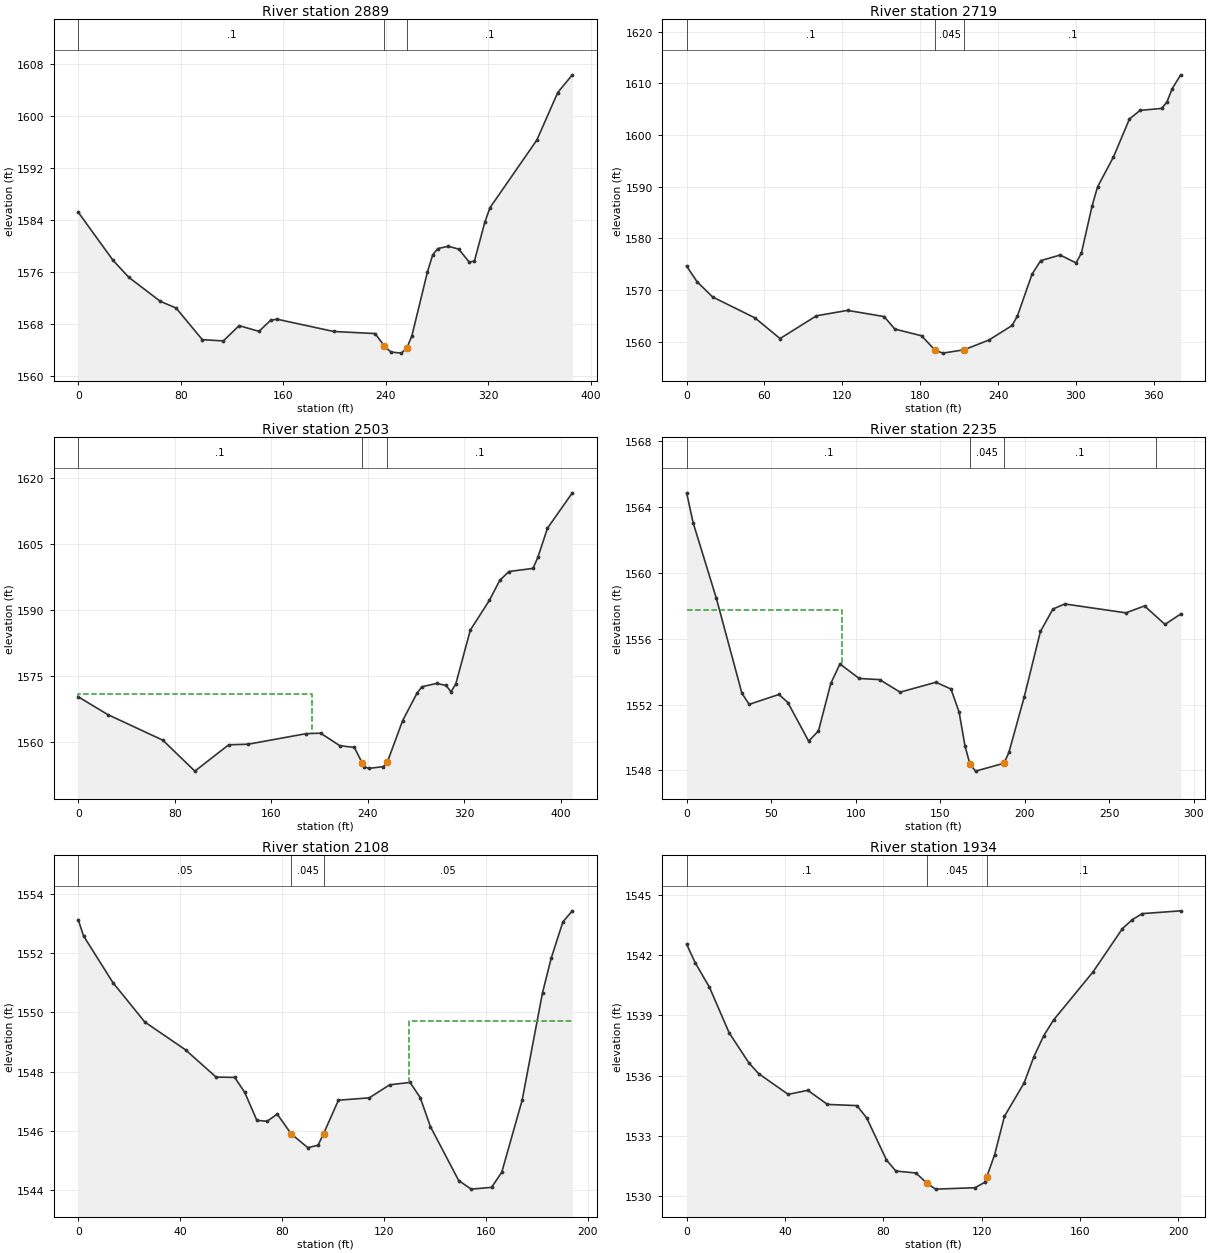
Type RM Length L Ch R = 1 ,2889    ,170.9,170.4,168.1
XS GIS Cut Line= 3
2196173.91019157693738.6493285012196218.59235632693936.063256398
2196251.90087913694116.416721389
#Sta/Elev= 30
       0 1585.18    27.2 1577.77    39.5 1575.16    64.1 1571.47    76.4 1570.44
    96.9 1565.57   113.3 1565.38   125.6 1567.73   141.1 1566.85   150.2 1568.55
   155.2 1568.72   199.5 1566.83   231.8 1566.51   239.1 1564.57   244.2 1563.66
   252.4  1563.5   256.7 1564.35   260.5 1566.15   272.7 1576.03   276.8 1578.64
   280.8 1579.59     289 1579.94   297.1  1579.5   305.2 1577.53   309.3 1577.64
   317.4  1583.6   321.5 1585.88   358.1 1596.29   374.4  1603.6   385.8 1606.32
#Mann= 3 ,-1,0
       0      .1       0   239.1    .045       0   256.7      .1       0
Bank Sta=239.1,256.7
XS Rating Curve= 0 ,0
Exp/Cntr(USF)=0,0
Exp/Cntr=0.3,0.1

Type RM Length L Ch R = 1 ,2719    ,209.7,215.8,217.9
XS GIS Cut Line= 3
2196044.20877178693773.1413519762196045.83357777693919.373891158
2196099.45217547694147.659132882
#Sta/Elev= 30
       0 1574.63       8 1571.62      20 1568.66    52.7  1564.6      72 1560.61
     100 1565.01     124 1566.06   152.2 1564.86   160.4 1562.44     181 1561.15
   191.5 1558.35   197.4 1557.79   213.8 1558.44   232.9 1560.32   250.8 1563.14
   254.9 1564.99   266.1 1573.03   272.8 1575.68   287.8 1576.77   300.1 1575.24
   304.2 1577.18   312.4 1586.24   316.6 1589.94   328.9 1595.75   341.2 1603.09
   349.4 1604.75   365.9 1605.13     370 1606.32   374.1 1608.94   380.7 1611.63
#Mann= 3 ,-1,0
       0      .1       0   191.5    .045       0   213.8      .1       0
Bank Sta=191.5,213.8
XS Rating Curve= 0 ,0
Exp/Cntr(USF)=0,0
Exp/Cntr=0.3,0.1

Type RM Length L Ch R = 1 ,2503    ,256.5,268,273.5
XS GIS Cut Line= 3
2195878.65190379693804.7542756482195866.39342238693975.258608028
2195857.47816317 694213.74179188
#Sta/Elev= 30
       0 1570.36    24.5 1566.32    70.1 1560.51    96.7 1553.48   124.7 1559.46
   140.8 1559.59   188.9 1561.99   200.9  1562.1   216.9 1559.25   228.9 1558.87
   235.21555.438   236.9 1554.47   240.9 1554.11   252.9  1554.5   256.11555.443
   268.9 1564.94   280.9 1571.22   284.9 1572.64     297 1573.39     305 1572.94
     309 1571.48     313 1573.29     325 1585.49   340.9  1592.3   349.4 1596.79
     357 1598.81     377 1599.52     381 1602.03     389 1608.66   409.6 1616.68
#Mann= 3 ,-1,0
       0      .1       0   235.2    .045       0   256.1      .1       0
#XS Ineff= 2 , 0
          193.73    1571
Permanent Ineff=
       F       F
Bank Sta=235.2,256.1
XS Rating Curve= 0 ,0
Exp/Cntr(USF)=0,0
Exp/Cntr=0.3,0.1

Type RM Length L Ch R = 1 ,2235    ,131.9,126.9,117.3
XS GIS Cut Line= 3
2195737.81256152693763.5253362562195676.61424387693897.766807225
2195596.33257986694018.189303242
#Sta/Elev= 30
       0 1564.84     3.9 1563.01    17.6 1558.44    32.7 1552.69      37 1552.01
    54.6 1552.61    59.9 1552.12    72.2 1549.78      78  1550.4    85.3 1553.28
    90.7 1554.46   102.1 1553.58   114.2 1553.51   126.3 1552.75   147.5 1553.35
   156.4 1552.94   161.2 1551.54   164.7 1549.48   167.6 1548.39   170.9 1547.96
   187.8 1548.44   190.7 1549.11   199.7 1552.45   209.3 1556.43   216.7 1557.79
   223.7  1558.1   259.9 1557.56   270.9 1557.98     283 1556.86   292.3 1557.49
#Mann= 4 ,-1,0
       0      .1       0   167.6    .045       0   187.8      .1       0
  277.53     .05       0
#XS Ineff= 2 , 0
           91.88 1557.72
Permanent Ineff=
       F       F
Bank Sta=167.6,187.8
XS Rating Curve= 0 ,0
Exp/Cntr(USF)=0,0
Exp/Cntr=0.3,0.1

Type RM Length L Ch R = 1 ,2108    ,170.3,173.6,172.2
XS GIS Cut Line= 4
2195549.01495578693791.0724151852195547.28797874693858.424519793
2195545.12925744693922.7544145792195544.69751318693984.925588064
#Sta/Elev= 30
       0 1553.13     2.1 1552.58    13.6 1551.01    26.1 1549.68    42.1 1548.74
    54.1 1547.82    61.4 1547.81    65.3 1547.31    70.1 1546.36    74.1 1546.33
    78.1 1546.57    83.6  1545.9    90.1 1545.44    94.1 1545.52    96.31545.916
   102.1 1547.04   114.2 1547.12   122.2 1547.56   130.2 1547.64   134.2 1547.13
   138.2 1546.15   149.3 1544.33   154.2 1544.04   162.2  1544.1   166.2 1544.61
   174.2 1547.04   182.2 1550.67   185.6 1551.83   190.2 1553.06   193.9 1553.43
#Mann= 3 ,-1,0
       0     .05       0    83.6    .045       0    96.3     .05       0
#XS Ineff= 2 , 0
                          129.89         1549.71
Permanent Ineff=
       F       F
Bank Sta=83.6,96.3
XS Rating Curve= 0 ,0
Exp/Cntr(USF)=0,0
Exp/Cntr=0.3,0.1

Type RM Length L Ch R = 1 ,1934    ,73.9,77,80
XS GIS Cut Line= 3
2195386.32487491693811.917775943 2195389.9528083693960.231916332
2195389.07447276694012.886171633
#Sta/Elev= 30
       0 1542.53     3.5 1541.61     9.3 1540.39    17.3 1538.13    25.3 1536.64
    29.3  1536.1    41.3 1535.07    49.3 1535.27    57.3 1534.57    69.3 1534.51
    73.3 1533.89    81.3 1531.81    85.1 1531.26    93.3 1531.16    97.8 1530.65
   101.3 1530.36   117.3 1530.43   121.3  1530.7   122.11530.974   125.3 1532.07
   129.3 1533.98   137.3 1535.64   141.3 1536.95   145.3 1537.99   149.3 1538.77
   165.3 1541.15   177.3 1543.31   181.3 1543.75   185.3 1544.05     201 1544.19
#Mann= 3 ,-1,0
       0      .1       0    97.8    .045       0   122.1      .1       0
Bank Sta=97.8,122.1
XS Rating Curve= 0 ,0
Exp/Cntr(USF)=0,0
Exp/Cntr=0.3,0.1

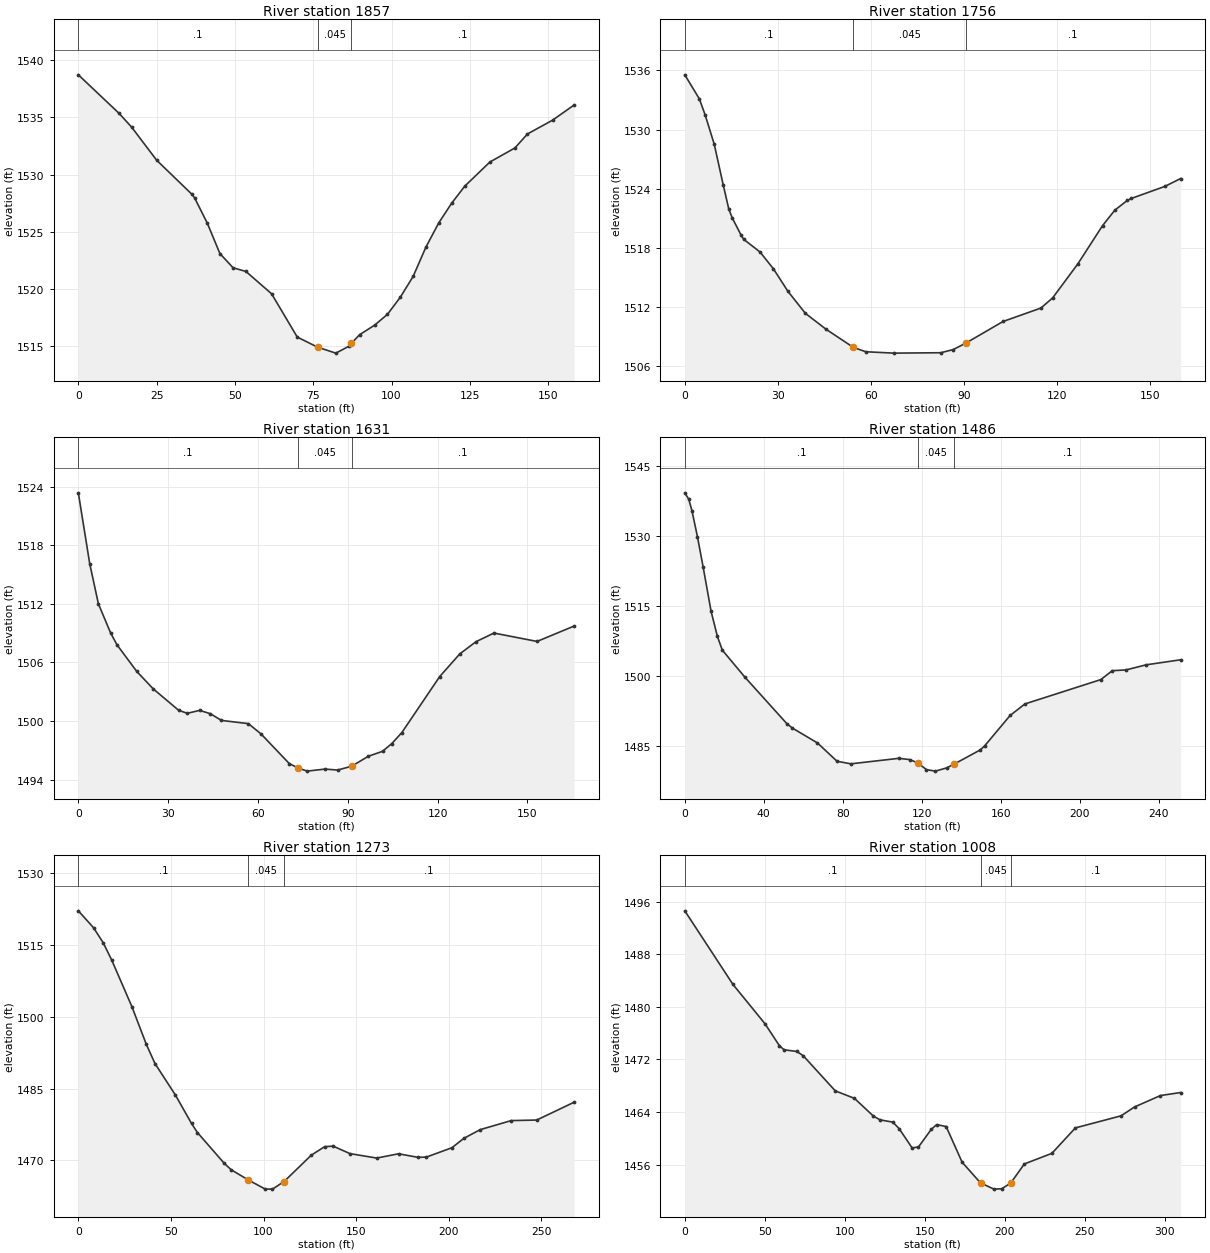
Type RM Length L Ch R = 1 ,1857    ,108.7,101.4,99.4
XS GIS Cut Line= 4
 2195331.5012079693828.3057858512195326.45338267693870.753407118
2195307.40931475693950.8302710212195308.09765455 693984.10002823
#Sta/Elev= 30
       0  1538.7      13 1535.34      17 1534.14      25 1531.25    36.2 1528.29
    37.1 1527.97    41.2 1525.74    45.2  1523.1    49.4 1521.86    53.5 1521.54
    61.7 1519.59    69.9 1515.81    76.41514.929    82.2 1514.41    86.4 1515.01
    87.2 1515.27    89.8 1516.02    94.6 1516.85    98.7  1517.8   102.8 1519.29
   106.9 1521.11     111 1523.68   115.1 1525.79   119.2  1527.5   123.4 1528.99
   131.4 1531.09   139.4 1532.32   143.4 1533.54   151.4 1534.74   158.3 1536.07
#Mann= 3 ,-1,0
       0      .1       0    76.4    .045       0    87.2      .1       0
Bank Sta=76.4,87.2
XS Rating Curve= 0 ,0
Exp/Cntr(USF)=0,0
Exp/Cntr=0.3,0.1

Type RM Length L Ch R = 1 ,1756    ,102,125,129.2
XS GIS Cut Line= 3
2195253.43712773693801.2593716212195231.84991472693834.359764911
 2195219.8570186693954.288726108
#Sta/Elev= 30
       0 1535.56     4.7 1533.12     6.6 1531.46     9.5 1528.52    12.4 1524.39
    14.2 1521.94    15.3 1521.05    18.2 1519.28      19 1518.88    24.3 1517.58
    28.6 1515.88    33.3 1513.59    38.9 1511.37    45.5 1509.77    54.4 1507.91
    58.4 1507.47    67.4 1507.33    82.6 1507.37    86.6 1507.69    90.6 1508.33
   102.7 1510.54   114.9  1511.9   118.7 1512.93   126.8 1516.37   134.8 1520.26
   138.8 1521.84   142.8 1522.82   144.1 1523.02   154.9 1524.24     160 1525.04
#Mann= 3 ,-1,0
       0      .1       0    54.4    .045       0    90.6      .1       0
Bank Sta=54.4,90.6
XS Rating Curve= 0 ,0
Exp/Cntr(USF)=0,0
Exp/Cntr=0.3,0.1

Type RM Length L Ch R = 1 ,1631    ,142.3,144.6,145.1
XS GIS Cut Line= 4
2195192.51321545693766.2401149512195166.60855983693796.941929018
2195108.08322676693869.8587374262195089.37430882693895.763393044
#Sta/Elev= 30
       0  1523.4     3.8 1516.14     6.7 1512.02    10.8 1509.02    12.9 1507.82
    19.5 1505.09      25  1503.3    33.5  1501.1    36.4 1500.79    40.5 1501.09
    44.1 1500.75    47.8 1500.06    56.8 1499.73      61 1498.68    70.5 1495.62
    73.4 1495.19    76.4 1494.86    82.4 1495.07    86.6 1494.97    91.31495.366
    96.9 1496.39   101.6 1496.89   104.7 1497.69     108 1498.79   120.7 1504.56
   127.4 1506.88   132.8 1508.13   138.8 1509.02   153.2 1508.16   165.6 1509.74
#Mann= 3 ,-1,0
       0      .1       0    73.4    .045       0    91.3      .1       0
Bank Sta=73.4,91.3
XS Rating Curve= 0 ,0
Exp/Cntr(USF)=0,0
Exp/Cntr=0.3,0.1

Type RM Length L Ch R = 1 ,1486    ,215.6,213.5,206.4
XS GIS Cut Line= 3
2195111.90615966693671.8050096742194986.74745979693796.003107992
2194944.50250403693857.745735647
#Sta/Elev= 30
       0 1539.19       2 1537.82     3.6 1535.41     6.4 1529.82     9.3 1523.31
    13.3 1513.89    16.5  1508.5      19 1505.57    30.3 1499.85    51.7 1489.84
    54.5  1488.9    67.2 1485.72    77.1 1481.81    84.1 1481.26   108.3 1482.43
   113.9 1482.17     118 1481.46   122.4 1480.01   126.9  1479.7   132.6 1480.39
   136.5 1481.22   149.6 1484.23   151.8 1485.07   164.8 1491.62   172.3 1494.07
   210.7 1499.27   216.5 1501.17   223.4 1501.33   233.7 1502.43   251.1  1503.5
#Mann= 3 ,-1,0
       0      .1       0     118    .045       0   136.5      .1       0
Bank Sta=118,136.5
XS Rating Curve= 0 ,0
Exp/Cntr(USF)=0,0
Exp/Cntr=0.3,0.1

Type RM Length L Ch R = 1 ,1273    ,258.8,264.7,270.1
XS GIS Cut Line= 3
2194980.39503613 693493.733714682194960.14740152 693527.22727601
2194848.81810214693726.817641562
#Sta/Elev= 30
       0 1522.06     8.2 1518.54    13.4 1515.42      18 1511.81    28.9  1502.1
    36.7 1494.22    41.4  1490.2    52.3 1483.72    61.1 1477.72    64.3 1475.82
    78.8 1469.39    82.6 1468.04    91.8 1465.93   100.9 1464.03   104.8 1464.02
   111.1 1465.61   125.8 1471.11     133 1472.88   137.6 1472.98   146.7 1471.42
   161.1  1470.5   172.9 1471.39   183.4 1470.65   187.9  1470.7   201.7 1472.65
   208.1  1474.6     217 1476.43   233.7 1478.31   247.5 1478.43   267.7 1482.15
#Mann= 3 ,-1,0
       0      .1       0    91.8    .045       0   111.1      .1       0
Bank Sta=91.8,111.1
XS Rating Curve= 0 ,0
Exp/Cntr(USF)=0,0
Exp/Cntr=0.3,0.1

Type RM Length L Ch R = 1 ,1008    ,252.1,238.2,216.7
XS GIS Cut Line= 4
2194918.26574093693423.1492922572194761.41965365693420.824288671
2194691.96824037693472.3141295542194677.90528759693537.490492454
#Sta/Elev= 30
       0 1494.59    30.1  1483.4    50.1 1477.43    59.2 1474.06    62.1 1473.46
    70.1  1473.2    74.1 1472.54    94.1 1467.21   106.1 1466.07   117.9 1463.38
   122.1  1462.8   130.1 1462.46   134.1 1461.44   142.1 1458.54   146.1 1458.68
   154.1 1461.36   157.5 1462.08   163.4 1461.79   173.4 1456.36  184.91 1453.21
   193.3 1452.27   198.2 1452.33   203.8  1453.2   212.3  1456.1   229.5 1457.71
   244.2 1461.58   272.8 1463.42   281.2 1464.77   297.4  1466.5     310 1466.96
#Mann= 3 ,0,0
       0      .1       0  184.91    .045       0   203.8      .1       0
Bank Sta=184.91,203.8
XS Rating Curve= 0 ,0
Exp/Cntr(USF)=0,0
Exp/Cntr=0.3,0.1

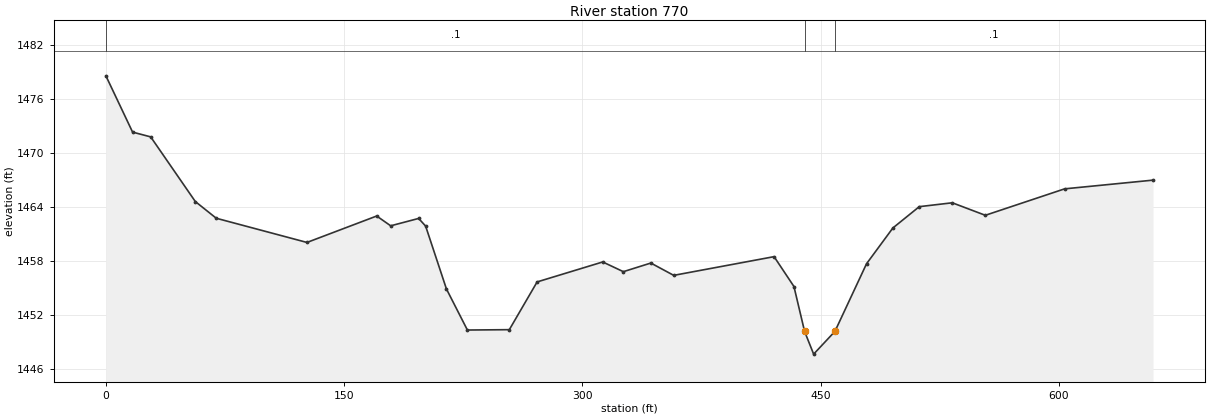
Type RM Length L Ch R = 1 ,770     ,,,
XS GIS Cut Line= 4
2194883.48644968693235.1256969612194615.75838322693356.440210645
2194514.07587844693425.472578008 2194580.0706143693658.788507409
#Sta/Elev= 30
       0 1478.55    16.8 1472.29    28.2 1471.76    56.3 1464.57    69.5 1462.71
   126.6 1460.02   170.5 1462.96   179.3 1461.87   196.9 1462.69   201.3 1461.84
   214.4 1454.85   227.6 1450.28     254 1450.32   271.5 1455.63   312.8 1457.85
   325.8 1456.77   343.1 1457.73   357.5 1456.36   420.7 1458.44   433.2 1455.12
  439.91 1450.12   445.6  1447.6  459.01 1450.13   478.9 1457.65   495.5 1461.63
   512.1    1464   532.9 1464.43   553.7 1463.04   603.6 1465.98   659.3 1466.95
#Mann= 3 ,-1,0
       0      .1       0  439.91    .045       0  459.01      .1       0
Bank Sta=439.91,459.01
XS Rating Curve= 0 ,0
Exp/Cntr(USF)=0,0
Exp/Cntr=0.3,0.1
LCMann Table=0

Chan Stop Cuts=-1
Use User Specified Reach Order=0
Composite Channel Slope=5